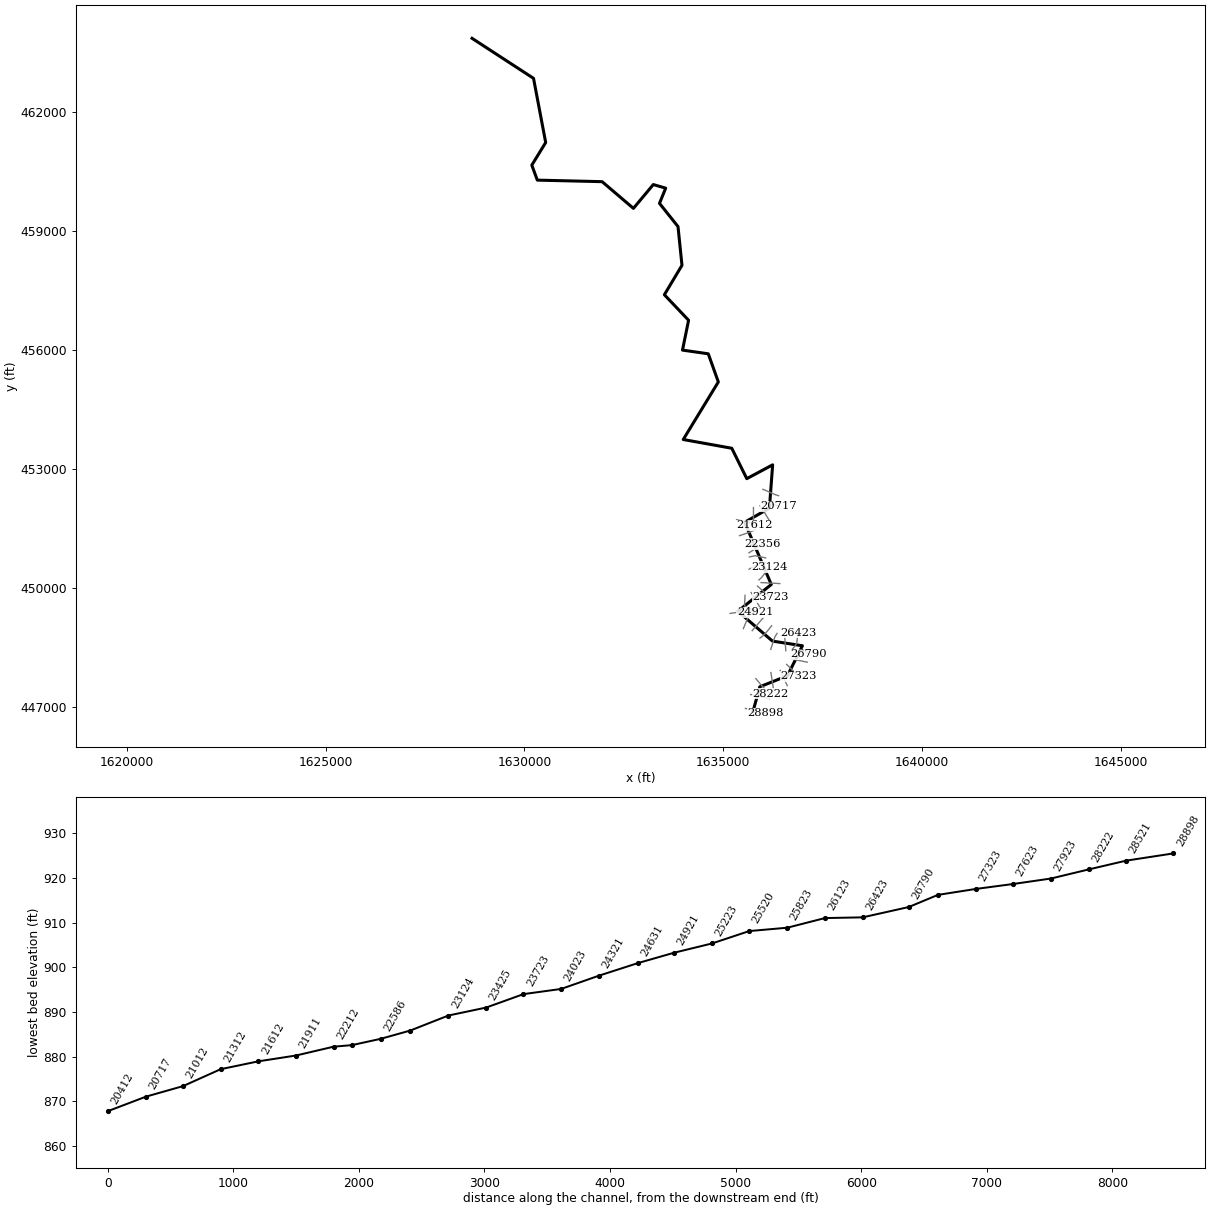
--- LynCmpRn.prj (project) ---

Proj Title=LynCmpRn
Current Plan=p01
Default Exp/Contr=0,0
English Units
Geom File=g01
Flow File=f01
Plan File=p01
BEGIN DESCRIPTION:
---------- MODELED AS PART OF WVEM CTP PROGRAM, 2025----------
Stream Name: Lynn Camp Run
Flood Zone: AFH
Marshall County, WV
HEC-RAS Version: RAS 6.6
Vertical Datum: NAVD88
Projection: NAD 1983 StatePlane West Virginia N FIPS 4701 (US Feet)
Terrain: 1-meter West Virginia FEMA R3 South Central (collected 2018-2019)
Land Use: 2024 NLCD
Hydrologic Method:
Duda et al., "Estimation of magnitude and frequency of floods for rural, unregulated streams in and near Virginia and West Virginia." September 8, 2025.
Additional Model Notes:
None
END DESCRIPTION:
DSS Export Rating Curves= 0
DSS Export Rating Curve Sorted= 0
DSS Export Volume Flow Curves= 0
DXF OffsetX= 0
DXF OffsetY= 0
DXF ScaleX= 0
DXF ScaleY= 0

--- LynCmpRn.p01 (plan) ---

Plan Title=Floodplain
Program Version=6.60
Short Identifier=Floodplain
Geom File=g01
Flow File=f01
Subcritical Flow
K Sum by GR= 0
Std Step Tol= 0.01
Critical Tol= 0.01
Num of Std Step Trials= 20
Max Error Tol= 0.3
Flow Tol Ratio= 0.001
Split Flow NTrial= 30
Split Flow Tol= 0.02
Split Flow Ratio= 0.02
Log Output Level= 0
Friction Slope Method= 1
Unsteady Friction Slope Method= 2
Unsteady Bridges Friction Slope Method= 1
Parabolic Critical Depth
Global Vel Dist= 0 , 0 , 0
Global Log Level= 0
CheckData=False
Encroach Param=-1 ,0,0, 0
Flow Ratio Tolerance=0.1
Flow Ratio Min Ratio=0.5
Flow Ratio Max Ratio=4
Flow Ratio Max Iterations= 10
Mapping Interval=1HOUR
Computation Time Step Use Courant=        0
Computation Time Step Use Time Series=    0
Computation Time Step Count To Double=0
Computation Time Step Max Doubling=0
Computation Time Step Max Halving=0
Computation Time Step Residence Courant=0
Run HTab= 0
Run UNet= 0
Run Sediment= 0
Run PostProcess= 0
Run WQNet= 0
Run RASMapper=-1
UNET Theta= 0
UNET Theta Warmup= 0
UNET ZTol= 0
UNET ZSATol= 0
UNET MxIter= 0
UNET Max Iter WO Improvement= 0
UNET MaxInSteps= 0
UNET DtIC= 0
UNET DtMin= 0
UNET MaxCRTS= 0
UNET WFStab= 0
UNET SFStab= 0
UNET WFX= 1
UNET SFX= 1
UNET Gravity=32.17405
UNET 1D Methodology=Finite Difference
UNET DSS MLevel= 1
UNET Pardiso=0
UNET DZMax Abort= 0
UNET Use Existing IB Tables= 0
UNET Froude Reduction=False
UNET Froude Limit= 0
UNET Froude Power= 0
UNET D1 Cores= 0
UNET WindReference=Eulerian
UNET WindDragFormulation=Hsu (1988)
UNET D2 Coriolis=0
UNET D2 Cores= 0
UNET D2 Theta= 1
UNET D2 Theta Warmup= 1
UNET D2 Z Tol= 0.01
UNET D2 Volume Tol= 0.01
UNET D2 Max Iterations= 20
UNET D2 Advanced Convergence=0
UNET D2 WS Max Tol=0.15
UNET D2 WS RMS Tol=0.002
UNET D2 WS Stall Tol=1
UNET D2 Equation= 0
UNET D2 RampUpFraction=0.1
UNET D2 TimeSlices= 1
UNET D2 Turbulence Formulation=Non-Conservative (original)
UNET D2 Eddy Viscosity=0.3
UNET D2 Transverse Eddy Viscosity=0.1
UNET D2 Smagorinsky Mixing=0
UNET D2 BCVolumeCheck=0
UNET D2 Cores=0
UNET D2 SolverType=PARDISO (Direct)
UNET D2 Minimum Iterations= 3
UNET D2 Maximum Iterations= 30
UNET D2 Restart Number= 10
UNET D2 Relaxation Coeff=1.3
UNET D2 SOR Precondition Iterations= 10
UNET D2 ILUT Maximum Fill= 8
UNET D2 ILUT Tolerance=1E-08
UNET D2 Convergence Tolerance=0.00001
PS Theta= 1
PS WS Tol= 0.01
PS Volume Tol= 0.01
PS Max Iterations= 20
PS Equation= 0
PS Advance Time Step=-1
PS Target Courant=0.9
PS Time Slices= 1
PS Iterate With 2D=0
PS Project Initial WSE from DS=-1
PS Ramp Up Initial WSE from US=-1
PS Cores=0
UNET D1D2 MaxIter= 0
UNET D1D2 ZTol=0.01
UNET D1D2 QTol=0.1
UNET D1D2 MinQTol=1
Write IC File= 0
Write IC File at Fixed DateTime=0
Write IC File at Sim End=0
Echo Input=False
Echo Parameters=False
Echo Output=False
Write Detailed= 0
HDF Write Warmup=0
HDF Write Time Slices=0
HDF Flush=0
HDF Compression= 1
HDF Chunk Size= 1
HDF Spatial Parts= 1
HDF Use Max Rows=0
HDF Fixed Rows= 1
Calibration Method= 0
Calibration Iterations= 20
Calibration Max Change=0.05
Calibration Tolerance=0.2
Calibration Maximum=1.5
Calibration Minimum=0.5
Calibration Optimization Method= 1
WQ AD Non Conservative
WQ ULTIMATE=-1
WQ Max Comp Step=1HOUR
WQ Output Interval=15MIN
WQ Output Selected Increments= 0
WQ Create Restart=0
WQ Fixed Restart=0
WQ System Summary=0
WQ Write To DSS=0
Sorting and Armoring Iterations= 10
XS Update Threshold= 0.02
Bed Roughness Predictor= 0
Processes Affected by Predictor=Sediment Only
Hydraulics Update Threshold= 0.02
Energy Slope Method= 1
Volume Change Method= 1
Sediment Retention Method= 0
Sediment TS Multiplier= 1
Warm Up Method= 0
XS Weighting Method= 0
Number of US Weighted Cross Sections= 1
Number of DS Weighted Cross Sections= 1
Upstream XS Weight=0
Main XS Weight=1
Downstream XS Weight=0
Number of DS XS's Weighted with US Boundary= 1
Upstream Boundary Weight= 1
Weight of XSs Associated with US Boundary= 0
Number of US XS's Weighted with DS Boundary= 1
Downstream Boundary Weight= 0.5
Weight of XSs Associated with DS Boundary= 0.5
Percentile Method= 0
Sediment Output Level= 3
Mass or Volume Output= 0
Output Increment Type= 1
Profile and TS Output Increment= 1
Transport Output Increment 1
XS Output Flag= 0
XS Output Increment= 10
Read HDF5 Sediment Hotstart= 0
Sediment Hotstart Type= 0
Write Gradation File= 0
Read Gradation Hotstart= 0
Write HDF5 File= 1
Write Binary Output= 1
Write DSS Sediment File= 0
DSS Sediment Output Type= 1
SV Curve= 0
Specific Gage Flag= 0
Subcell Erosion Methods= 0
Subcell Deposition Methods= 0
Advection Scheme= 1
Matrix Solver= 0
Implicit Weighting Factor= 1
Maximum Outer Loop Convergence Iterations= 5
Convergence Maximum Absolute= 0.001
Convergence RMSE= 0.0001
Grain Fractions Max Abs Error= 0.001
Max Subgrid Regions= 1
Max Subgrid Length Scale= 3.402823E+38
Initial Layer Thickness= 3
Min Layer Thickness= 0.1
Max Layer Thickness= 6
Number of Layers= 5

--- LynCmpRn.f01 (steady flow) ---

Flow Title=Flow
Program Version=6.60
Number of Profiles= 1
Profile Names=P100yr
River Rch & RM=LynCmpRn,Main,28898
    3470
River Rch & RM=LynCmpRn,Main,17412
    3950
Boundary for River Rch & Prof#=LynCmpRn,Main            , 1
Up Type= 0
Dn Type= 3
Dn Slope=0.005426
DSS Import GetInterval= 0
DSS Import GetPeak= 0
DSS Import FillOption= 0

--- LynCmpRn.g01 (geometry) ---

Geom Title=Geometry
Program Version=6.60

River Reach=LynCmpRn        ,Main
Reach XY= 30
1635746.80016809446893.374666659     1635918.806      447519.862
     1636614.563      447797.284     1636991.064      448552.487
     1636236.961      448670.281     1635366.693       449421.17
     1636208.646      450094.732     1635537.902      451660.272
        1636161.      452016.957     1636242.465      453106.828
     1635591.845       452758.95     1635214.243      453524.062
     1633993.367      453744.2381634876.10042431455192.843994235
     1634622.864      455901.963     1633974.377      455994.849
1634127.74454767456746.199917963     1633518.624      457388.371
     1633961.442      458129.043     1633861.746      459103.983
      1633396.03       459688.77     1633551.034      460071.348
1633240.13875815460162.1708301731632740.04203302459562.833702775
      1631952.38      460234.807     1630322.725      460273.558
     1630183.926      460650.499     1630533.301      461220.314
1630227.19640555 462835.93652444     1628681.098      463842.773

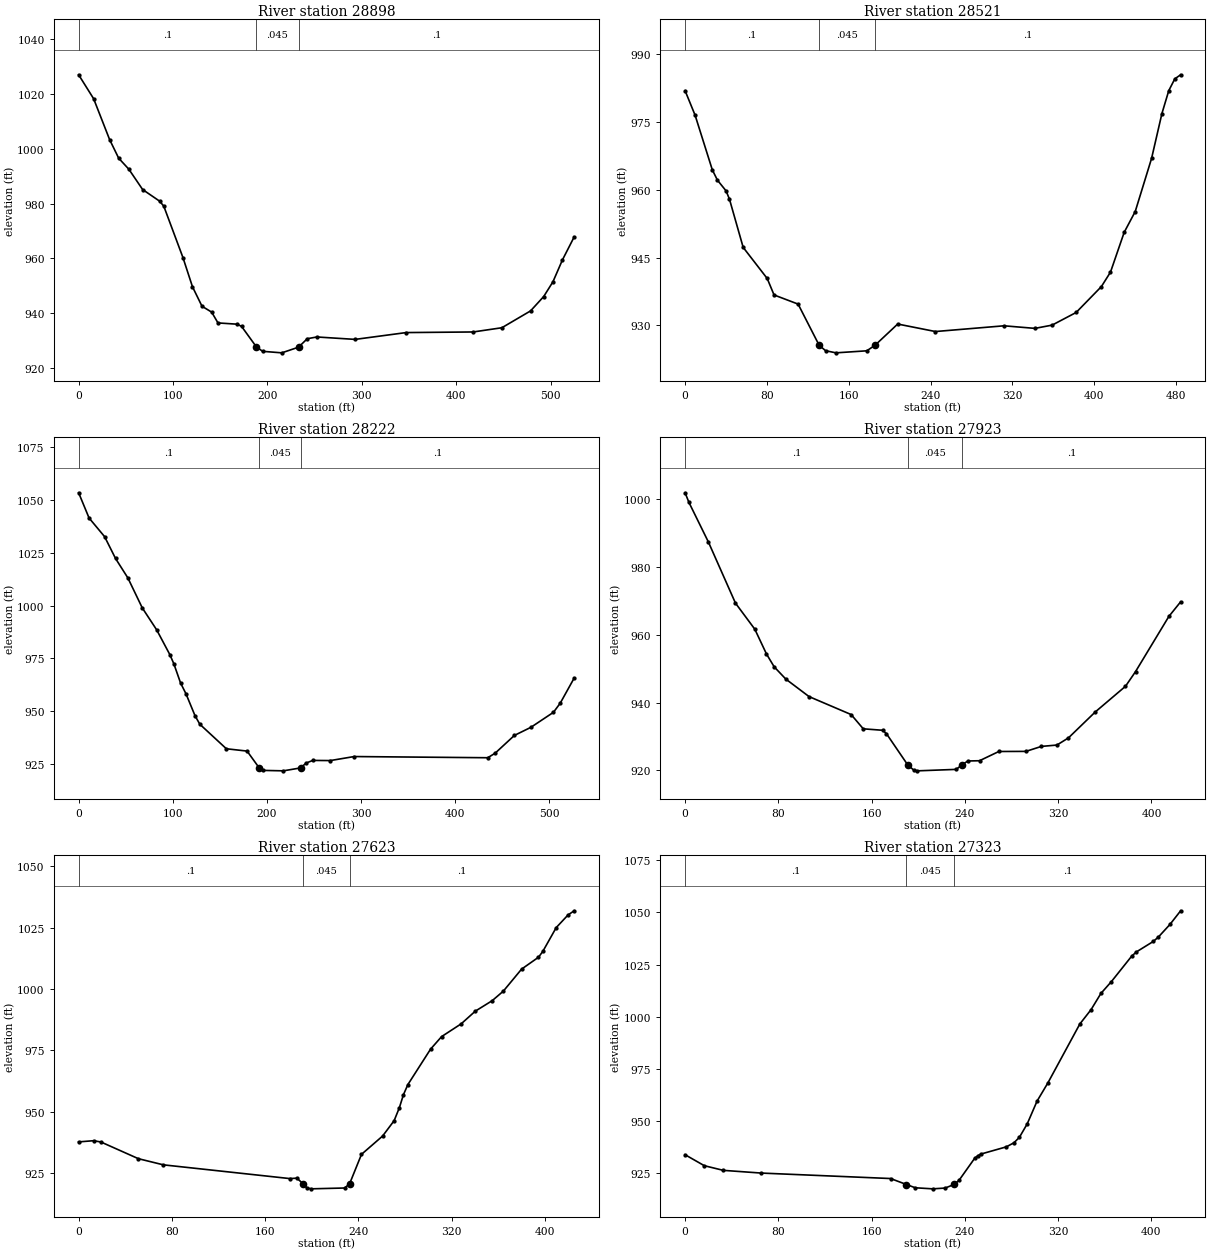
Type RM Length L Ch R = 1 ,28898   ,376,376.5,377.3
XS GIS Cut Line= 2
1635558.14054969446975.8200986451636067.91069792446850.505011181
#Sta/Elev= 30
       0 1027.01    15.9 1018.26    32.8 1003.36    42.4  996.57    53.2  992.53
    67.8  985.11    85.8  980.87    90.2  979.04   110.5  960.28   120.6  949.61
   130.7   942.5   140.9  940.37   147.6  936.42   167.9  935.96   172.6  935.15
   188.2  927.71   194.9  926.05   215.2   925.5   232.9927.5621   242.2  930.66
   252.4  931.29   292.9  930.41     347   932.9   417.9  933.12   448.3  934.66
   478.7  940.81   492.6  946.04   502.4  951.43   512.5  959.45   524.9  967.82
#Mann= 3 ,-1,0
       0      .1       0   188.2    .045       0   232.9      .1       0
Bank Sta=188.2,232.9
XS Rating Curve= 0 ,0
Exp/Cntr=0.3,0.1

Type RM Length L Ch R = 1 ,28521   ,313,299,282.9
XS GIS Cut Line= 6
1635691.88282342447325.4943317481635777.41217993447307.027833254
1635850.72305693447291.1994528331635948.47023676447270.094836251
1636021.78111376447254.266127751 1636165.6233688447223.392957644
#Sta/Elev= 30
       0  981.95     9.8  976.51    26.6  964.43    31.6  962.14    40.1  959.75
    43.4  957.91    56.8  947.24    80.3  940.35      87   936.7   110.5  934.68
  131.06925.5724   137.4  924.35   147.5  923.88   177.7  924.33  185.81925.5716
   207.9  930.26   244.8   928.6   311.9  929.87   342.1   929.3   358.9  930.02
   382.4  932.82   407.1  938.56     416  941.76   429.4  950.58   440.2  955.19
   456.2  966.97   466.3   976.9     473  981.97   478.9  984.58   484.6  985.48
#Mann= 3 ,-1,0
       0      .1       0  131.06    .045       0  185.81      .1       0
Bank Sta=131.06,185.81
XS Rating Curve= 0 ,0
Exp/Cntr(USF)=0,0
Exp/Cntr=0.3,0.1

Type RM Length L Ch R = 1 ,28222   ,310.7,299.5,285.9
XS GIS Cut Line= 6
1635818.78695743447726.0110138361635875.10213351447659.041659594
1635923.37205009447601.639215335 1635988.5507255447525.791926086
1636041.00928201447471.9121125941636182.14164687447346.751584222
#Sta/Elev= 30
       0 1053.27    11.1 1041.34    27.6 1032.53    39.2 1022.23    52.3 1013.04
    67.6  998.88    82.9  988.51    96.9  976.79   101.1  972.51   108.3  963.37
     114  958.32   123.6  947.97   128.7  943.93   156.9  932.34   178.9  931.24
  191.81923.2842   195.7  922.12   217.4  921.91  235.64923.2823   241.7   925.6
   248.7  926.83   267.3  926.76   292.6  928.66   434.5   928.1   442.3  930.22
   462.8  938.64   480.3  942.46   504.3  949.56   511.5  953.88   526.3  965.74
#Mann= 3 ,-1,0
       0      .1       0  191.81    .045       0  235.64      .1       0
Bank Sta=191.81,235.64
XS Rating Curve= 0 ,0
Exp/Cntr(USF)=0,0
Exp/Cntr=0.3,0.1

Type RM Length L Ch R = 1 ,27923   ,294.2,300,305.8
XS GIS Cut Line= 6
1636198.07360043447878.2843313371636211.72022668447791.855370343
1636223.41738176447717.7728413341636239.01347917447618.996464089
1636250.71063426447544.9142631741636264.35758859447458.484974086
#Sta/Elev= 30
       0 1001.93     3.3  999.08      20  987.39    43.2  969.37    59.8  961.67
    69.8  954.36    76.4  950.57    86.4  946.95   106.3  941.79   142.4  936.49
   152.8  932.28   169.4  931.85   172.7  930.84  190.81 921.696     196  920.12
   199.3  919.88   232.5  920.31  237.67 921.696   242.5  922.79   252.5  922.86
   269.1  925.59   292.3  925.62   305.6  927.09   318.9  927.49   328.8  929.61
   351.8  937.26   377.7  944.83   386.3  949.15   414.9  965.44     425  969.75
#Mann= 3 ,-1,0
       0      .1       0  190.81    .045       0  237.67      .1       0
Bank Sta=190.81,237.67
XS Rating Curve= 0 ,0
Exp/Cntr(USF)=0,0
Exp/Cntr=0.3,0.1

Type RM Length L Ch R = 1 ,27623   ,293,300,306
XS GIS Cut Line= 6
1636431.04951243447934.3928149191636467.77516076447854.962855667
1636499.28395601447786.9026243391636541.29633917447696.156086668
1636572.80546251 447628.095855341636609.52356492447548.682956427
#Sta/Elev= 30
       0  937.78    12.8  938.26    19.1  937.74    51.3  930.93    72.7  928.43
   181.1  922.84   187.2  923.01  192.57920.6897   195.6  919.12   199.2  918.66
   228.1     919  232.37 920.691   242.6  932.71   260.7  940.16   270.6  946.43
   275.1  951.73   278.6  957.03   282.4  961.14   301.8  975.53   311.3  980.66
   328.1  985.86   340.2  991.02   354.7  995.29   364.3   999.2   379.9 1008.14
   394.4 1012.98   398.1 1015.35   409.6 1025.05   419.7 1030.18     425  1031.9
#Mann= 3 ,-1,0
       0      .1       0  192.57    .045       0  232.37      .1       0
Bank Sta=192.57,232.37
XS Rating Curve= 0 ,0
Exp/Cntr(USF)=0,0
Exp/Cntr=0.3,0.1

Type RM Length L Ch R = 1 ,27323   ,281.9,300,311.1
XS GIS Cut Line= 6
1636594.28179751448082.4774925111636658.17865135448022.466457665
1636712.04206067447970.1742394271636780.68037485447897.449975416
1636832.15894642447842.9071055051636892.21722525447779.273374513
#Sta/Elev= 30
       0  933.89    16.5  928.63    32.8   926.4    65.3   925.1   176.3  922.48
  189.94919.6197   197.5  918.05   212.4  917.54   223.1  917.91  230.75919.6208
     235  921.58   248.5  932.21   250.9  933.28   253.5  934.16   275.6  937.66
   282.2  939.63   286.9  942.28   293.6  948.73     302  959.59   311.3  968.32
   338.7  996.55   348.4 1003.48   356.8 1011.21   365.8 1016.88   383.2 1029.08
   387.3 1031.13   401.7 1036.11   406.1 1038.23     416 1044.25   425.2 1050.82
#Mann= 3 ,-1,0
       0      .1       0  189.94    .045       0  230.75      .1       0
Bank Sta=189.94,230.75
XS Rating Curve= 0 ,0
Exp/Cntr(USF)=0,0
Exp/Cntr=0.3,0.1

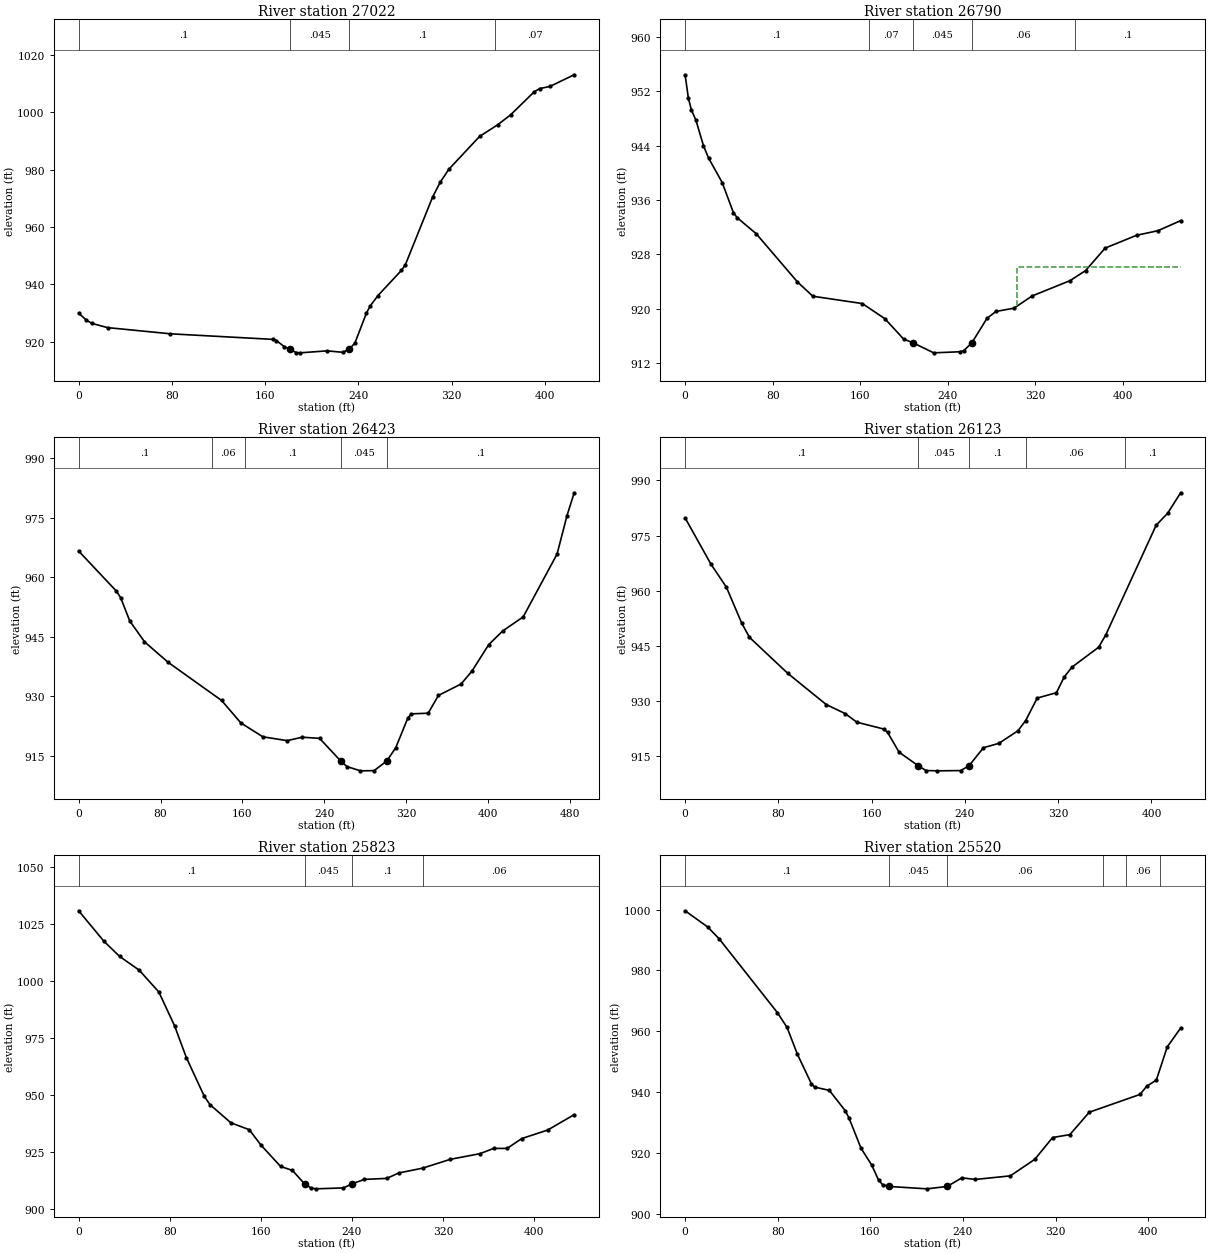
Type RM Length L Ch R = 1 ,27022   ,227.3,232.5,252.6
XS GIS Cut Line= 6
1636697.69530459448229.5415028331636782.81882201448209.061228842
 1636855.8915105448192.0438744281636953.85325684448171.954675749
1637027.33670567448156.9501125961637113.06783342448139.444898263
#Sta/Elev= 30
       0  930.06     6.6   927.6    11.3  926.47    24.8     925    78.8  922.84
   166.4  920.91   169.7  920.47   176.4  918.38  181.08 917.528   186.5  916.33
   189.8  916.22   213.3  916.91   226.7   916.4  232.28917.5271     237  919.64
   246.8  929.95   250.1  932.52   256.8  936.16   276.9   944.9   280.3  946.89
   303.7  970.47   310.4  975.73   317.6   980.1   343.9   991.5   359.4  995.55
   370.5     999   390.8 1007.04   395.5 1008.17   404.2  1008.9   425.1 1012.97
#Mann= 4 ,-1,0
       0      .1       0  181.08    .045       0  232.28      .1       0
  357.58     .07       0
Bank Sta=181.08,232.28
XS Rating Curve= 0 ,0
Exp/Cntr(USF)=0,0
Exp/Cntr=0.3,0.1

Type RM Length L Ch R = 1 ,26790   ,348.2,366.9,394.1
XS GIS Cut Line= 6
1636741.93602501448440.2981089931636838.58200026448410.155810885
1636891.86341351448390.7885857321637004.76704485448425.621413577
1637104.36885601448389.1117137991637157.25783087 448342.14545772
#Sta/Elev= 30
       0  954.41       3  950.98     5.7  949.27     9.9  947.72    16.8  943.98
    21.4  942.17    33.9  938.56    44.2   934.1    47.7  933.37    64.9  931.04
   102.6  923.95   116.7  921.83     162  920.75   182.6  918.52   199.7  915.53
   208.4914.9686   227.2   913.5   251.2  913.66   254.7  913.82  262.05914.9689
   275.9  918.57   284.1  919.59   300.6  920.07   317.2  921.87   351.8  924.12
   366.1  925.61   383.9  928.91   412.6  930.79   432.2  931.47   452.9  932.95
#Mann= 5 ,-1,0
       0      .1       0  167.93     .07       0   208.4    .045       0
  262.05     .06       0  356.08      .1       0
#XS Ineff= 2 , 0
                          303.61           926.2
Permanent Ineff=
       F       F
Bank Sta=208.4,262.05
XS Rating Curve= 0 ,0
Exp/Cntr(USF)=0,0
Exp/Cntr=0.3,0.1

Type RM Length L Ch R = 1 ,26423   ,297,300.5,306.3
XS GIS Cut Line= 6
1636718.13194351448444.1247350871636804.54056334448544.434573844
1636848.20156525448622.2628302571636861.16971518448721.423065007
1636871.65394618448795.6870240871636883.88522093448882.327926919
#Sta/Elev= 30
       0  966.56    36.9  956.45    41.1  954.79    49.9  948.97    64.3  943.71
    87.6  938.49   139.7  928.91   158.5  923.25     180  919.76   203.7   918.8
   218.5  919.66   235.4  919.37  256.11913.6518   262.1  912.27   275.3  911.19
   288.6  911.24  300.99 913.651   309.8  917.02   321.6  924.49     325  925.54
   341.5  925.71   351.5  930.19   373.6  933.06   384.2  936.29   400.6  942.97
   414.4  946.45   434.3  949.97   467.4   965.8   477.1  975.48   484.1  981.23
#Mann= 5 ,-1,0
       0      .1       0     130     .06       0   162.4      .1       0
  256.11    .045       0  300.99      .1       0
Bank Sta=256.11,300.99
XS Rating Curve= 0 ,0
Exp/Cntr(USF)=0,0
Exp/Cntr=0.3,0.1

Type RM Length L Ch R = 1 ,26123   ,305.1,300,288.2
XS GIS Cut Line= 6
1636573.93078834 448426.946291761636566.95311201448514.167902082
1636560.97215284448588.9289074241636552.99775934448688.610466585
1636547.01712826448763.3718000051636540.03912383448850.593082249
#Sta/Elev= 30
       0  979.79    22.2   967.2    35.4  960.97    48.6  951.16    55.2  947.32
    88.1  937.52     121  929.06   137.4  926.57   147.3  924.25   170.3   922.4
   173.6  921.52   183.5  916.11  200.17912.3601   206.6  911.12   216.4  911.03
   236.2   911.1   243.4912.3606   255.9  917.32   269.1   918.5   285.5  921.93
   292.1  924.71     302  930.81   318.5  932.28     325  936.46   331.6  939.17
   354.7  944.64   360.8  947.99     404  977.79   413.9  981.08     425  986.62
#Mann= 5 ,-1,0
       0      .1       0  200.17    .045       0   243.4      .1       0
   292.5     .06       0   377.5      .1       0
Bank Sta=200.17,243.4
XS Rating Curve= 0 ,0
Exp/Cntr(USF)=0,0
Exp/Cntr=0.3,0.1

Type RM Length L Ch R = 1 ,25823   ,301,302.6,285.5
XS GIS Cut Line= 6
1636193.85871384448460.8638748381636220.85242626448544.096319929
1636243.98984717448615.4380407481636274.84050725448710.560225844
1636300.84964159448781.8924322581636352.92565292 448863.31156075
#Sta/Elev= 30
       0 1030.97    22.1 1017.65    35.9 1010.96    53.2 1004.89    70.4  995.31
    84.2  980.52    94.6  966.49   110.3  949.54   115.3  945.85   133.7  937.86
   149.8  934.84   160.1  928.09   177.3  918.71   187.7  916.96  198.33911.0873
   204.1  909.21   208.4  908.87   232.5  909.28   240.2  911.09   250.9  913.02
   270.6  913.46     281  915.83     302  917.95   326.4  921.84   352.4  924.31
   364.3  926.62   376.2  926.62   389.1  930.95   411.8  934.67   435.1  941.45
#Mann= 4 ,-1,0
       0      .1       0  198.33    .045       0   240.2      .1       0
   302.5     .06       0
Bank Sta=198.33,240.2
XS Rating Curve= 0 ,0
Exp/Cntr(USF)=0,0
Exp/Cntr=0.3,0.1

Type RM Length L Ch R = 1 ,25520   ,297.3,297.4,298
XS GIS Cut Line= 6
1635924.41863592448745.3596969251635994.83450559448801.158141762
1636049.05290109448853.8660415861636115.37822776448928.887545094
1636162.05759634 448987.590511681636216.51713309449056.076923251
#Sta/Elev= 30
       0  999.59    19.6  994.24    29.5  990.33    79.8  966.06    88.1  961.21
    97.1  952.32   109.1   942.7   111.9  941.58   124.6  940.52   138.3  933.84
   141.6  931.43     152  921.45   161.2  915.96   167.1  911.03   170.7  909.46
   176.4   908.9   208.9  908.12  226.38908.8995   239.1  911.74   250.8  911.21
     281  912.39   302.1  917.83   317.5     925   332.4  925.96   349.2  933.33
   393.1  939.19   398.7  941.85   407.1  943.88   416.5   954.8   428.1  961.02
#Mann= 6 ,-1,0
       0      .1       0   176.4    .045       0  226.38     .06       0
   360.6      .1       0   380.6     .06       0   410.6      .1       0
Bank Sta=176.4,226.38
XS Rating Curve= 0 ,0
Exp/Cntr(USF)=0,0
Exp/Cntr=0.3,0.1

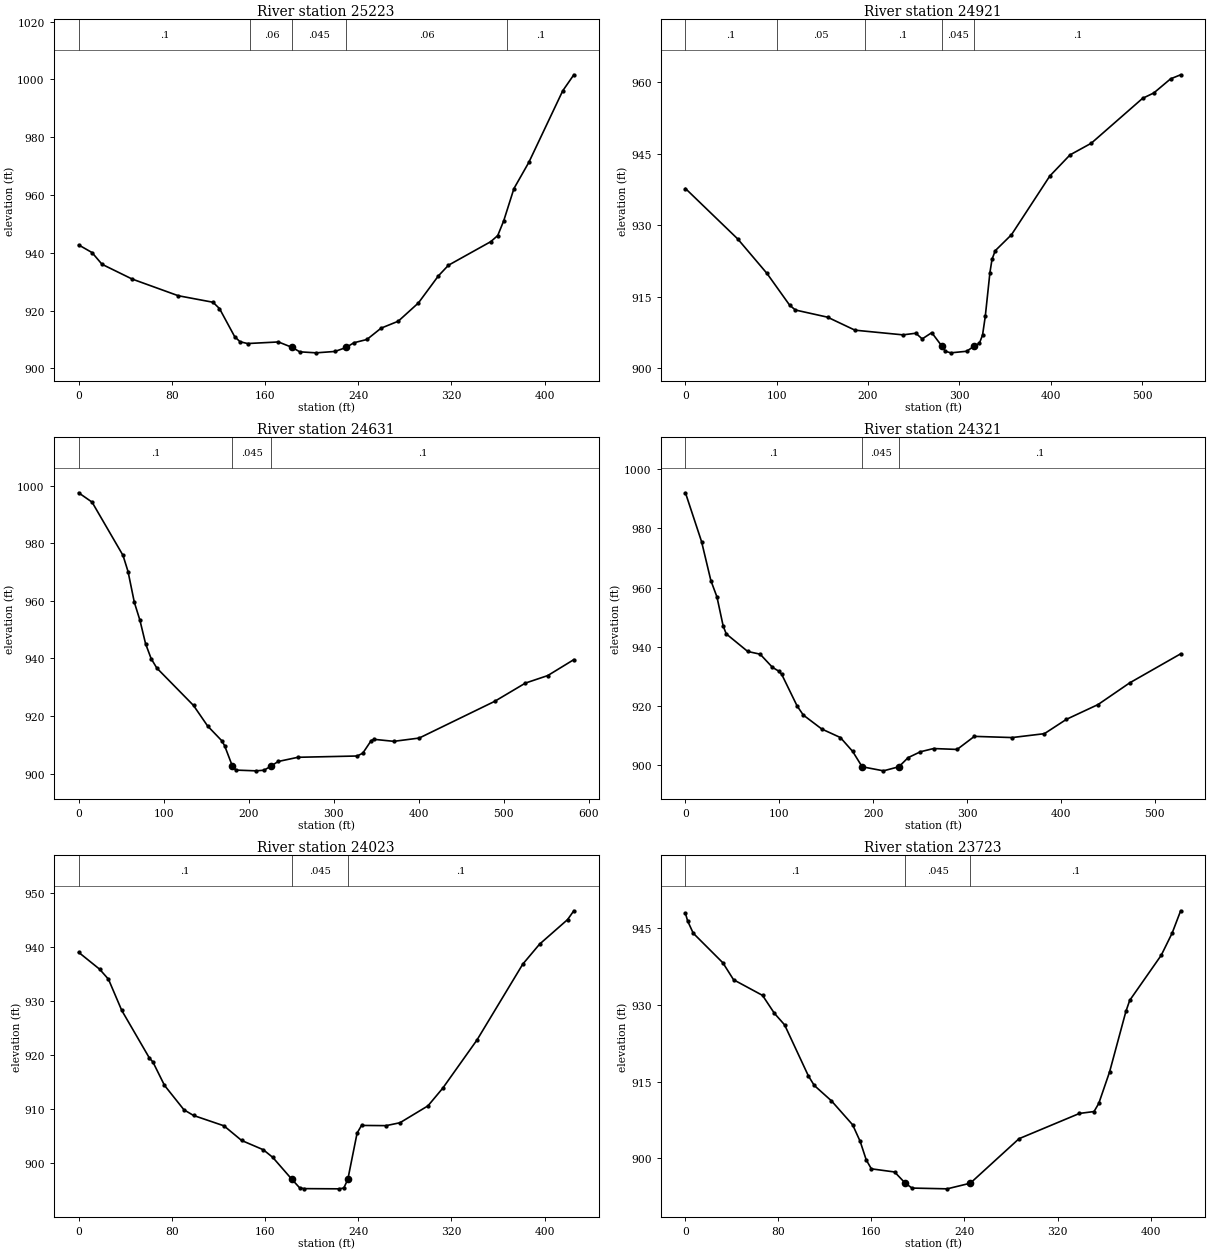
Type RM Length L Ch R = 1 ,25223   ,292.9,301.5,307.1
XS GIS Cut Line= 6
1635728.11850359448932.5125378371635784.85001743  448999.1292025
1635833.47688867 449056.229482011635898.31271701449132.362531841
1635946.93958826449189.4628113361636003.67110209449256.079475999
#Sta/Elev= 30
       0  942.72    11.5  940.07    20.1     936    45.9   930.9    85.5  925.12
   115.3  922.86   120.9  920.67   133.9  910.97   138.5  909.19     145  908.56
   171.5  909.11  183.42907.1892   189.8  905.69   203.8  905.34     220  905.82
  229.53 907.191   236.3  908.84   247.4  909.96   259.6  913.89   274.3  916.29
   291.6  922.61   308.8  932.01   317.4  935.68   353.7  943.84   359.7  945.96
   364.8  951.04   373.6  962.23   386.4  971.32   415.5   996.1     425 1001.63
#Mann= 5 ,-1,0
       0      .1       0   147.5     .06       0  183.42    .045       0
  229.53     .06       0   367.5      .1       0
Bank Sta=183.42,229.53
XS Rating Curve= 0 ,0
Exp/Cntr(USF)=0,0
Exp/Cntr=0.3,0.1

Type RM Length L Ch R = 1 ,24921   ,313.8,290.2,266.3
XS GIS Cut Line= 5
1635505.29307166448983.4326263831635572.68475933449146.373658672
1635601.05314092449216.0526531791635634.23745775449310.433697999
1635804.91623231449395.607286536
#Sta/Elev= 30
       0  937.72    57.3  927.14    89.3  919.92   114.1  913.27   120.4  912.25
   155.6  910.75   185.7  908.02   238.2  907.04   252.4  907.38   259.3  906.19
   269.8   907.5  280.78904.7044   284.6  903.61   290.6  903.27     308   903.6
  316.42904.7065   321.9  905.25   325.4  906.98   328.4  910.89   333.5   920.1
   335.8  922.88   339.3  924.68   357.1  928.03   399.1  940.34   421.2  944.76
   444.5  947.21   500.7  956.62     513  957.75   531.4  960.71   542.4  961.56
#Mann= 5 ,-1,0
       0      .1       0     100     .05       0  196.33      .1       0
  280.78    .045       0  316.42      .1       0
Bank Sta=280.78,316.42
XS Rating Curve= 0 ,0
Exp/Cntr(USF)=0,0
Exp/Cntr=0.3,0.1

Type RM Length L Ch R = 1 ,24631   ,349.4,309.7,275.7
XS GIS Cut Line= 4
1635170.81445251449366.9179177881635289.97309703449383.781424912
1635570.26120776449425.5942288341635748.71984035449427.158858255
#Sta/Elev= 30
       0  997.62    15.8  994.37    52.2  975.84    58.1  970.24    65.5  959.53
    72.1  953.27    78.7  945.15    85.3  939.92      92  936.65   135.1  923.66
   151.7  916.51   168.1  911.46   171.6  909.71  180.66 902.658   184.8  901.19
   208.5  900.93     218  901.14  226.57 902.659   234.6  904.18   257.8  905.64
   327.5  906.09   334.1  907.08     344  911.46   347.4  911.88   370.6  911.19
   400.4  912.33   489.1  925.09   525.3  931.45   551.5  934.05   582.2   939.6
#Mann= 3 ,-1,0
       0      .1       0  180.66    .045       0  226.57      .1       0
Bank Sta=180.66,226.57
XS Rating Curve= 0 ,0
Exp/Cntr(USF)=0,0
Exp/Cntr=0.3,0.1

Type RM Length L Ch R = 1 ,24321   ,282.9,298.6,307.1
XS GIS Cut Line= 6
1635547.07227775449821.2870070041635544.45154808449733.786853924
1635539.10608634449658.9776203331635534.74159376449559.034578756
 1635627.6538095449497.4884420041635777.41630526449463.105964839
#Sta/Elev= 30
       0  992.03    17.2  975.52    27.1  962.38    33.6  956.84    40.2  947.04
    43.5  944.37    66.4  938.43    79.6  937.52    92.7  933.08    99.3  931.82
   102.6   930.7     119  920.03   125.6  916.96   145.3  912.24   165.1  909.37
   178.2  904.68  188.28899.4976     211  898.12  227.45899.4975   237.3  902.58
   250.4  904.56   264.4  905.65   289.5  905.35   307.9  909.76   348.1  909.36
   382.5  910.67     406  915.52   439.7  920.51   473.4  927.83   527.7  937.64
#Mann= 3 ,-1,0
       0      .1       0  188.28    .045       0  227.45      .1       0
Bank Sta=188.28,227.45
XS Rating Curve= 0 ,0
Exp/Cntr(USF)=0,0
Exp/Cntr=0.3,0.1

Type RM Length L Ch R = 1 ,24023   ,290,300,305.8
XS GIS Cut Line= 6
1635703.36231951449891.7579946671635747.87633809449816.426780507
1635786.03111742449751.857355833 1635836.9037191449665.764680251
1635875.05849843449601.1949274991635919.57251701449525.864041418
#Sta/Elev= 30
       0  939.04      18  935.91    25.6  934.05      37  928.27    60.8  919.41
    63.7  918.72    73.7  914.36    90.4  909.83    98.6  908.78   124.7  906.86
   139.9  904.14   158.5  902.42   166.6  901.01     183  896.94   189.6  895.38
   193.3  895.21   223.8  895.17   227.6  895.33  231.05896.9396     239  905.51
   242.8  906.93   263.9  906.89   275.8  907.43   299.8  910.56   312.4  913.81
   341.9  922.78   381.2  936.85   395.6  940.55   419.6   945.1     425  946.74
#Mann= 3 ,-1,0
       0      .1       0     183    .045       0  231.05      .1       0
Bank Sta=183,231.05
XS Rating Curve= 0 ,0
Exp/Cntr(USF)=0,0
Exp/Cntr=0.3,0.1

Type RM Length L Ch R = 1 ,23723   ,278.7,297.5,309.4
XS GIS Cut Line= 6
1635860.83739826450054.8314874171635926.23588951449996.699713916
1635982.29187976449946.8727138341636057.03352818449880.436823085
1636113.85657726449831.3066720071636183.72618817449777.285782665
#Sta/Elev= 30
       0  947.96     1.9  946.47     6.7  944.08    32.2  938.28    41.4  934.96
    66.3   931.9    76.5  928.39    85.3  926.12   105.8   916.1   110.8  914.26
   125.6  911.24   143.8  906.55   150.3  903.29   155.5  899.67   159.9  897.93
   179.9  897.31  189.07895.1106   194.9  894.16   225.1  894.01  244.96895.1122
   286.9  903.83   338.9  908.78   351.4  909.15   355.5  910.75   364.8  916.93
   378.8  928.75   382.1  930.93   409.2  939.76   418.6  944.11   425.9  948.47
#Mann= 3 ,-1,0
       0      .1       0  189.07    .045       0  244.96      .1       0
Bank Sta=189.07,244.96
XS Rating Curve= 0 ,0
Exp/Cntr(USF)=0,0
Exp/Cntr=0.3,0.1

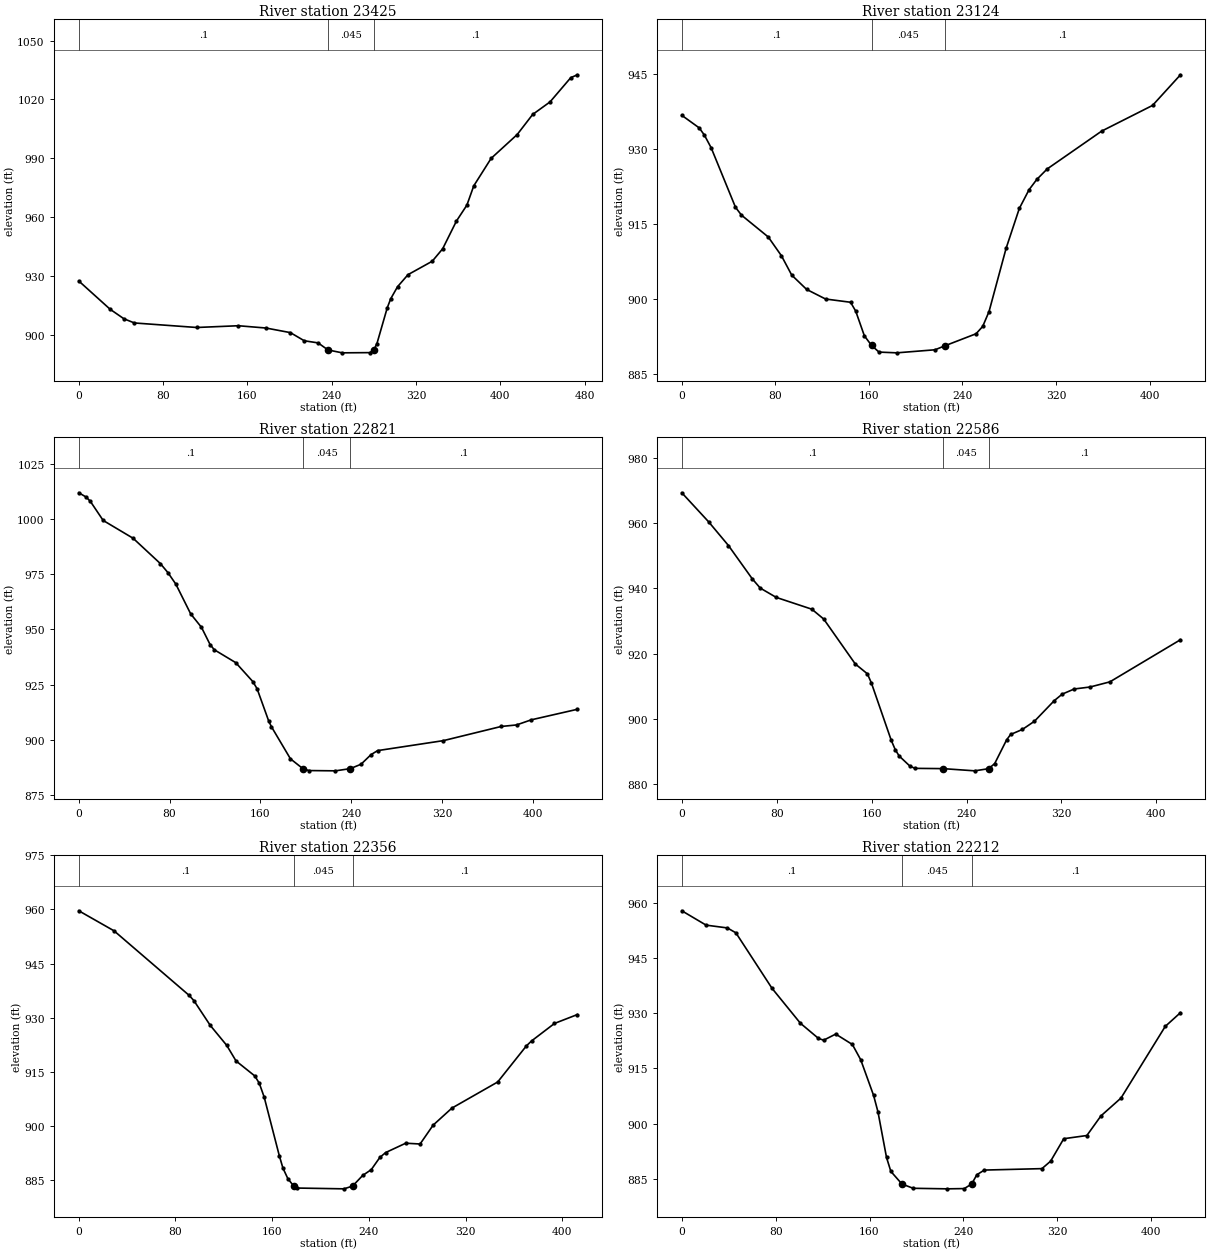
Type RM Length L Ch R = 1 ,23425   ,276.8,300.6,320.8
XS GIS Cut Line= 6
1635950.65381968450142.9707468451636069.93343675450136.325418919
1636160.70294026450128.708308175 1636260.8201941450127.386460423
1636335.66945384450122.6341733341636422.99375425450117.089893088
#Sta/Elev= 30
       0  927.58    29.8  913.16    42.9  908.32    52.8  906.21   111.9  903.91
   151.4   904.8   177.7  903.63   200.8  901.29     214  897.14   227.1  896.06
  236.43892.4792     250     891   276.3  891.11   279.9892.4827   282.9  895.67
   292.7  913.91     296  918.54   302.5  924.68   312.4   930.8   335.4  937.64
   345.3  943.99   358.4  958.13   368.3  966.22   374.8  976.02   391.3  990.03
     416 1002.14   430.7 1012.38   447.2 1018.77   466.9 1031.14   473.2 1032.58
#Mann= 3 ,-1,0
       0      .1       0  236.43    .045       0   279.9      .1       0
Bank Sta=236.43,279.9
XS Rating Curve= 0 ,0
Exp/Cntr(USF)=0,0
Exp/Cntr=0.3,0.1

Type RM Length L Ch R = 1 ,23124   ,313.1,303.3,288.3
XS GIS Cut Line= 6
1635897.16869043450209.3908895851635962.96285017450269.166032508
 1636008.7121025450328.5966879281636069.71066818450407.837999254
1636115.45959242450467.2689827531636168.83350143450536.604802087
#Sta/Elev= 30
       0  936.65    14.9  934.14    19.3   932.7    25.1  930.17    45.9  918.29
      51  916.72    73.9  912.36    85.2   908.6      94  904.74   106.7  901.89
   122.9  899.97   144.3  899.32   148.7  897.55   156.1  892.62  162.23 890.704
   168.6  889.37   183.8  889.22   216.5  889.83     225  890.63   251.6  893.03
   257.3   894.5   262.7  897.47   277.3   910.1   288.6  918.06   296.9  921.79
   303.5  923.84   312.4  925.94     359   933.5   402.5  938.63   426.4  944.75
#Mann= 3 ,-1,0
       0      .1       0  162.23    .045       0     225      .1       0
Bank Sta=162.23,225
XS Rating Curve= 0 ,0
Exp/Cntr(USF)=0,0
Exp/Cntr=0.3,0.1

Type RM Length L Ch R = 1 ,22821   ,243.4,234.8,214.9
XS GIS Cut Line= 6
1635649.97397484450480.7171185911635726.18478042450523.707518175
1635791.50814059450560.5565258411635881.29995576450604.913392499
1635957.66364817450626.8319838351636052.20873468450649.800441846
#Sta/Elev= 30
       0 1011.95     6.4 1010.04    10.2 1008.05    21.5   999.4    47.9  991.31
    71.9  979.83    78.5  975.77    85.5  970.54    98.6  957.04   108.1  950.94
   115.7  943.12   119.4  940.77   138.3  934.92   153.3  926.37   157.1  923.11
   167.4  908.37   169.8  905.82   186.5  891.31  197.42 886.866   202.7  885.99
   226.2  885.86  239.24886.8669   248.7  888.85   257.5   893.2   263.3  895.03
   321.3  899.56   372.2  905.98   385.7  906.67   398.7  908.99   439.4  913.78
#Mann= 3 ,-1,0
       0      .1       0  197.42    .045       0  239.24      .1       0
Bank Sta=197.42,239.24
XS Rating Curve= 0 ,0
Exp/Cntr(USF)=0,0
Exp/Cntr=0.3,0.1

Type RM Length L Ch R = 1 ,22586   ,210.7,230.9,242.7
XS GIS Cut Line= 3
1635656.43278186450788.8486684621635805.02810951450818.774116391
1636068.16566888450764.082780521
#Sta/Elev= 30
       0  969.32    22.6  960.41    39.3  953.14    59.4  942.91    66.1  940.08
    79.6  937.22   109.6   933.6   119.6  930.58   146.2   916.8   156.4  913.78
   159.8  910.96   176.5  893.39   179.9   890.5   183.2  888.56   192.4  885.41
   196.6  884.77   220.1  884.69   246.9  884.01  258.63  884.68   263.7  886.23
   273.7  893.47   277.1  895.16   287.1  896.72   297.2  899.22   313.9  905.54
   320.6  907.54   330.7  909.12   344.1  909.73   360.8  911.31   420.3  924.24
#Mann= 3 ,-1,0
       0      .1       0   220.1    .045       0  258.63      .1       0
Bank Sta=220.1,258.63
XS Rating Curve= 0 ,0
Exp/Cntr(USF)=0,0
Exp/Cntr=0.3,0.1

Type RM Length L Ch R = 1 ,22356   ,146.5,144,141.8
XS GIS Cut Line= 2
1635647.31428356450892.497684021 1635996.0027228 451113.02656274
#Sta/Elev= 30
       0  959.62    29.2  954.06    91.3  936.19    95.2  934.75   108.8  927.86
   122.4  922.34   130.1  918.02   145.6  913.87   149.3  911.88   153.4     908
   165.9  891.78   168.9  888.35     173   885.4   177.8  883.38   180.6  882.81
   219.4  882.59  226.52  883.35   234.9   886.3     242  887.91   249.1  891.29
   253.9  892.64   270.5  895.23   282.4  895.01   293.2  900.24   308.7  904.95
   346.6  912.19   370.4  922.21   374.7  923.58   393.6  928.41   412.6  930.88
#Mann= 3 ,-1,0
       0      .1       0   177.8    .045       0  226.52      .1       0
Bank Sta=177.8,226.52
XS Rating Curve= 0 ,0
Exp/Cntr(USF)=0,0
Exp/Cntr=0.3,0.1

Type RM Length L Ch R = 1 ,22212   ,304.1,300.4,297.7
XS GIS Cut Line= 6
  1635558.565365451031.4909514191635636.82800376451070.622106761
1635703.90989059451104.1630501751635793.35262509451148.884089336
 1635859.7068231451183.8804104181635935.98160492451226.987607673
#Sta/Elev= 30
       0   957.8    20.7   953.9    38.8  953.14    46.1  951.81    76.9  936.73
   101.1  927.24   116.5  923.12   120.9  922.64   131.2   924.3   145.4  921.47
   152.5  917.33   163.5  907.62   167.2  903.18   174.5  890.78   178.2  886.99
   187.6883.5699   197.2   882.4   226.1  882.25   240.8  882.32  247.13883.5712
   251.5  886.08   257.9  887.35     307  887.74   314.4  889.77   325.6  895.87
   345.3  896.74   357.3  902.07   374.4  906.92   412.1  926.38   425.1  930.12
#Mann= 3 ,-1,0
       0      .1       0   187.6    .045       0  247.13      .1       0
Bank Sta=187.6,247.13
XS Rating Curve= 0 ,0
Exp/Cntr(USF)=0,0
Exp/Cntr=0.3,0.1

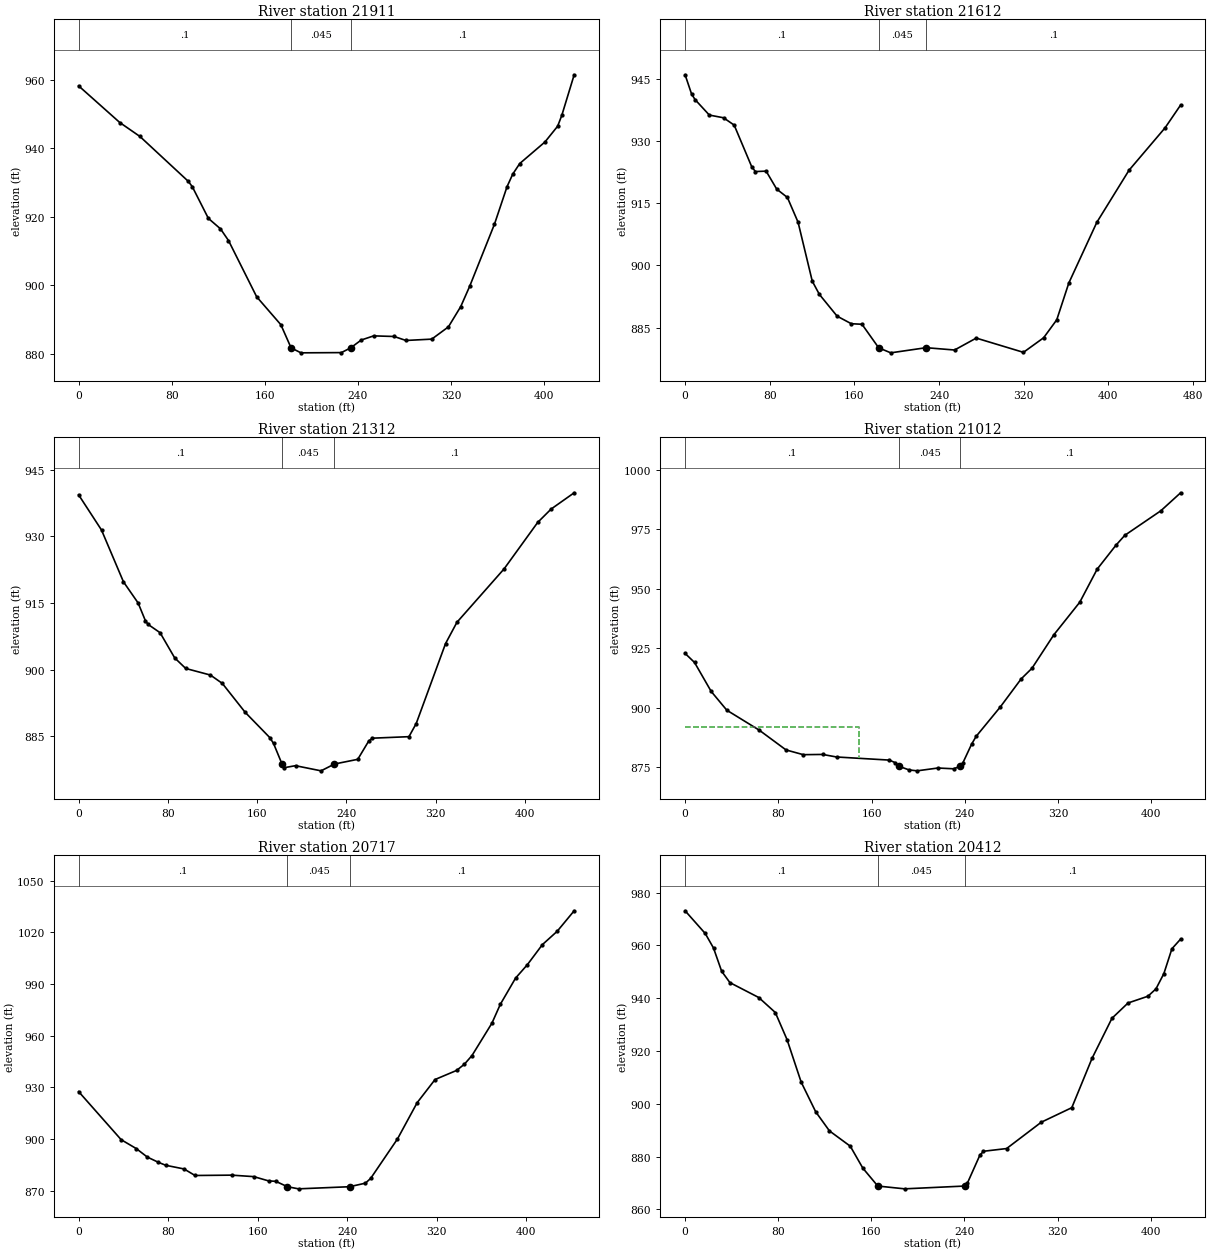
Type RM Length L Ch R = 1 ,21911   ,314.7,299.1,289.8
XS GIS Cut Line= 6
1635408.71067785451324.1209435911635491.72035433451351.791163832
1635562.87145875451375.5083080081635657.45919609451407.973138094
1635726.41082984451438.288694263 1635806.2620481451475.435273498
#Sta/Elev= 30
       0  958.15    35.4  947.45    52.7  943.39    94.2  930.32    97.7  928.74
   111.5   919.5   121.9  916.45   128.8  913.04     153  896.63   173.8  888.48
  182.61881.7102   191.1  880.27   225.8  880.34  233.75  881.71   242.9  884.01
   253.6  885.22   271.2  885.04   281.3  883.88   303.5  884.27   317.8  887.84
   328.4  893.76   336.1  899.69   357.4  917.81   368.2  928.74   373.1   932.4
   379.1  935.49   400.8  941.79   411.7  946.39   415.3  949.58   425.9  961.39
#Mann= 3 ,-1,0
       0      .1       0  182.61    .045       0  233.75      .1       0
Bank Sta=182.61,233.75
XS Rating Curve= 0 ,0
Exp/Cntr(USF)=0,0
Exp/Cntr=0.3,0.1

Type RM Length L Ch R = 1 ,21612   ,337.4,300.5,277.1
XS GIS Cut Line= 6
1635334.69671826451725.8570167571635420.19950001451707.268799335
1635493.48741117 451691.335760341635591.00722925451669.177668169
1635669.85024743451644.6222710911635776.56263243451582.858287007
#Sta/Elev= 30
       0  945.92     6.1  941.31     9.4  939.95    22.9  936.22    36.3  935.57
    46.4   933.8    63.1   923.7    66.5  922.62    76.6  922.72    86.6  918.39
    96.7  916.38   106.8  910.41   120.2  896.23   126.9  893.05   143.7   887.8
   157.1  885.98   167.2  885.85     183880.1786   194.4  878.97   227.8  880.21
   254.7  879.65   275.2  882.52   319.8  879.09   338.9   882.6   351.3  886.92
   362.7  895.78   389.2   910.4   419.6  922.93   453.7  933.15   468.4  938.64
#Mann= 3 ,-1,0
       0      .1       0     183    .045       0   227.8      .1       0
Bank Sta=183,227.8
XS Rating Curve= 0 ,0
Exp/Cntr(USF)=0,0
Exp/Cntr=0.3,0.1

Type RM Length L Ch R = 1 ,21312   ,283.1,300,310.8
XS GIS Cut Line= 6
1635759.71161626452032.5667051671635759.71161626451945.066880167
1635759.71161626451870.0670301771635759.71161626451770.066902086
1635759.71161626451695.0667240021635821.49331684451608.080677509
#Sta/Elev= 30
       0  939.32    20.5  931.41    40.2  919.74    53.3     915    59.9  910.97
    62.3  910.16      73   908.3    86.1  902.63      96  900.25   118.1  898.77
   128.8  896.89   149.3  890.38   171.4  884.68   174.7  883.38  182.32878.7475
   184.5  877.93   194.4  878.37   217.3  877.21  229.34878.7469   250.2   879.8
     260   883.9   263.3  884.56   296.1   884.9   302.6  887.85   328.9  905.85
   339.1  910.64   381.4  922.67   411.5  933.12   423.5  936.12   444.2  939.79
#Mann= 3 ,-1,0
       0      .1       0  182.32    .045       0  229.34      .1       0
Bank Sta=182.32,229.34
XS Rating Curve= 0 ,0
Exp/Cntr(USF)=0,0
Exp/Cntr=0.3,0.1

Type RM Length L Ch R = 1 ,21012   ,267.5,294.5,308
XS GIS Cut Line= 6
1635925.12663975452077.7828220871635974.38080634452005.374174252
 1636014.0034305451941.6948396711636066.83337735451856.789169595
1636106.45600151451793.1101630931636152.68261509451718.817660749
#Sta/Elev= 30
       0  922.83     8.1  919.02    22.4  906.82    35.8  898.93    63.6  890.54
    86.6  882.21   101.4  880.22     118  880.32   129.9  879.25   175.2  877.94
     180  876.91  183.81875.2872   192.1  873.81     199  873.42   216.9  874.61
   230.4  874.28  235.59875.2844   238.1  876.58   245.8  884.66   249.7  887.94
   270.5  900.36   288.3  912.11   297.6   916.6   316.3  930.65   338.6  944.39
   353.5  958.29   369.5  968.29   377.2  972.52   408.1  982.84   425.1  990.42
#Mann= 3 ,-1,0
       0      .1       0  183.81    .045       0  235.59      .1       0
#XS Ineff= 2 , 0
           149.5  892.02
Permanent Ineff=
       F       F
Bank Sta=183.81,235.59
XS Rating Curve= 0 ,0
Exp/Cntr(USF)=0,0
Exp/Cntr=0.3,0.1

Type RM Length L Ch R = 1 ,20717   ,305.7,305.5,291.3
XS GIS Cut Line= 6
1635974.81092359452147.329927087  1636073.749374452144.468384251
1636154.41522317 452145.424419091636251.63451692452119.560625672
1636321.57696234452092.4862047581636403.17653668452060.899325669
#Sta/Elev= 30
       0  927.52      38   899.6    51.5  894.45    61.4   889.5    71.2  886.49
    77.8  884.75    94.2  882.61     104  878.82   136.8  879.02   156.5  878.16
   169.7  875.69   176.2  875.43  186.57872.3006   196.5  871.07  242.11872.3004
   256.3  874.37     261  877.18   284.9  900.03   302.5  921.09   318.5  934.54
   337.7   939.8   344.7  943.42   351.5  948.46   369.3  967.23   376.8  978.18
   390.4  993.38     401 1001.22   414.4 1012.85   427.6 1020.58   442.8  1032.5
#Mann= 3 ,-1,0
       0      .1       0  186.57    .045       0  242.11      .1       0
Bank Sta=186.57,242.11
XS Rating Curve= 0 ,0
Exp/Cntr(USF)=0,0
Exp/Cntr=0.3,0.1

Type RM Length L Ch R = 1 ,20412   ,289.7,300,307.3
XS GIS Cut Line= 6
1635997.15996026452490.323335588  1636078.335979452457.443808168
1636146.87225926452426.9845515041636238.25331008452386.370459512
1636306.78926225452355.9102185821636391.14244001452330.373524249
#Sta/Elev= 30
       0  973.12    17.3  964.52    24.4  959.02    31.4  950.21    38.5  945.91
    63.3  940.26    77.5  934.59    87.6   924.3    99.7  908.24   112.2  896.98
     124  889.75   141.9  883.95   152.7  875.63  165.54868.8612   188.6   867.8
  240.19868.8592   242.5  869.95   253.2  880.52   256.3  882.03   276.2  883.06
     306  893.04   332.2  898.54   349.6  917.24   366.7   932.4   380.5  938.19
   397.6  940.75   404.5  943.54   411.3  949.33   418.2  958.73   425.7  962.41
#Mann= 3 ,-1,0
       0      .1       0  165.54    .045       0  240.19      .1       0
Bank Sta=165.54,240.19
XS Rating Curve= 0 ,0
Exp/Cntr(USF)=0,0
Exp/Cntr=0.3,0.1