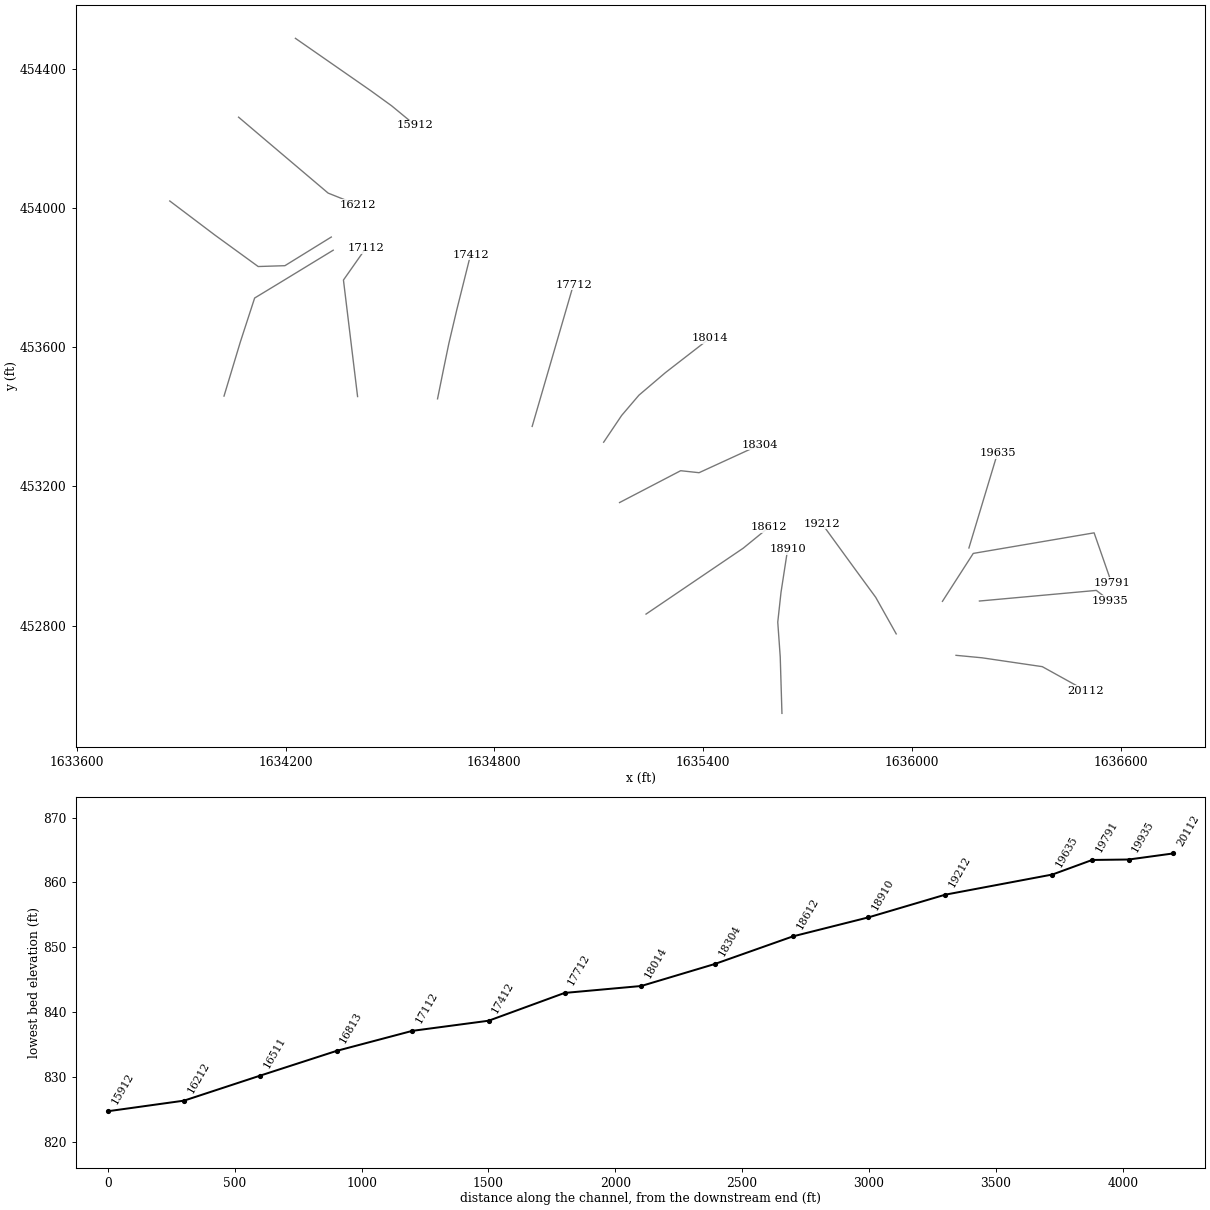
HEC-RAS study LynCmpRn.prj: LynCmpRn

--- LynCmpRn.g01 (geometry) --- (continued)

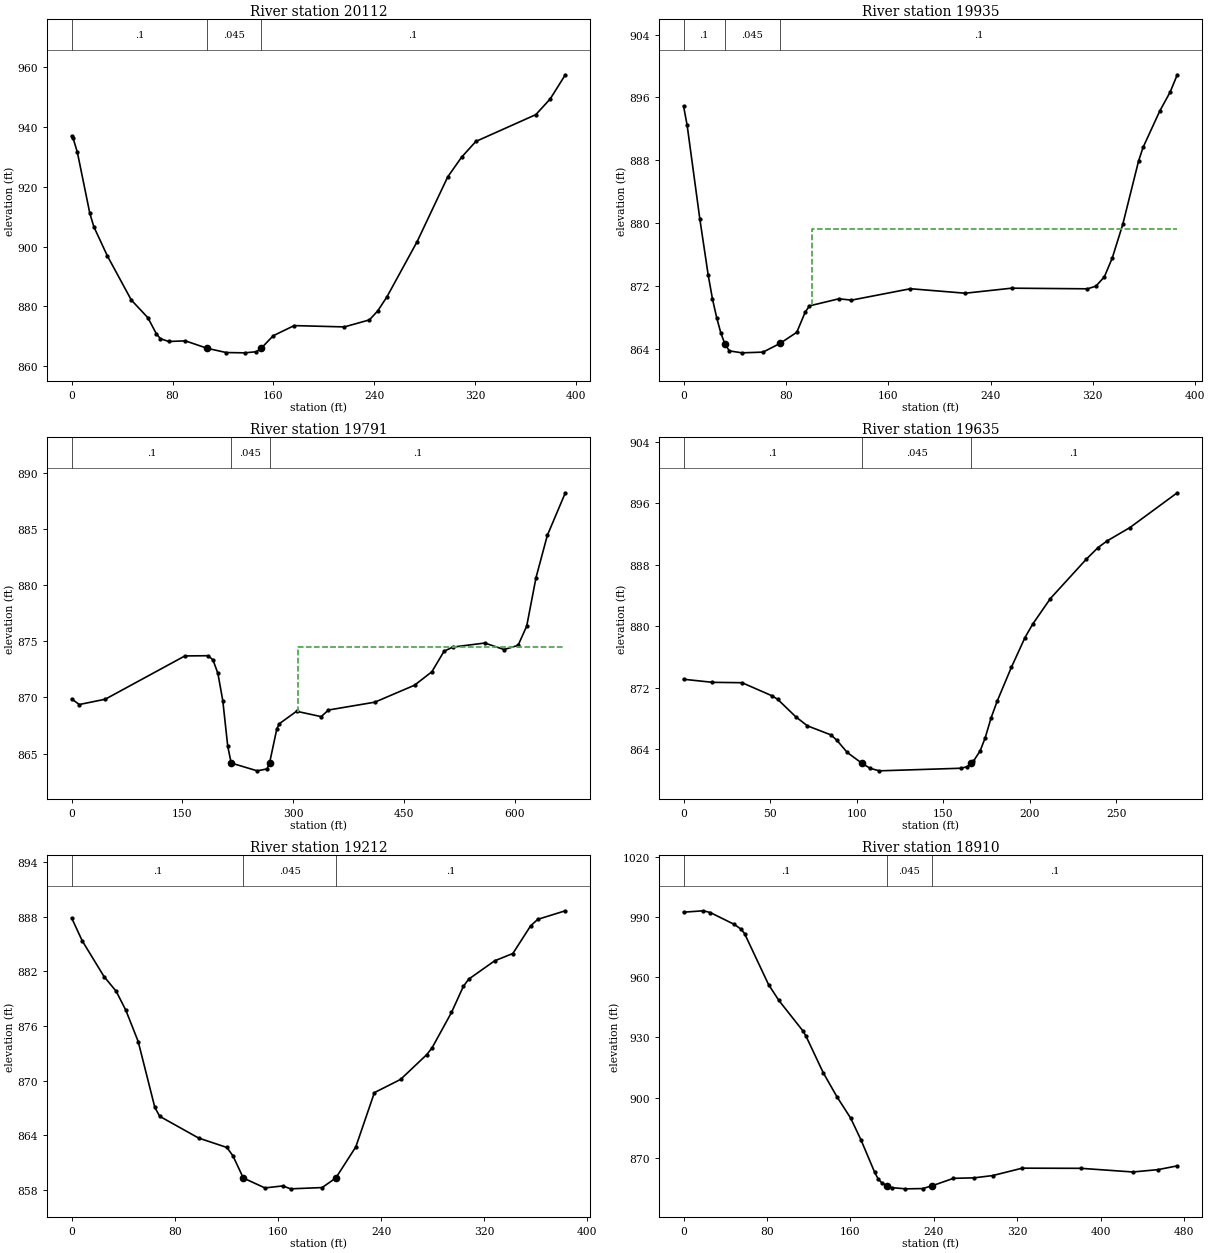
Type RM Length L Ch R = 1 ,20112   ,171.7,176.2,181.7
XS GIS Cut Line= 5
1636126.84802109452714.3196067511636201.60837026452707.203807339
1636300.54386793452692.6542957571636374.74614733452681.742244095
1636498.53587092452613.179799807
#Sta/Elev= 30
       0  937.01     1.2  936.25     4.5  931.65    14.4  911.19    17.6  906.67
    28.3  896.94    47.3  882.16    60.5  876.21    67.1  870.89    70.4  869.22
      77  868.27    90.2  868.48  107.58865.9764   122.6  864.57   137.1  864.47
   146.6  864.84  150.29865.9763   159.9   870.2   176.5  873.59   216.3  873.15
   236.2   875.5   242.8  878.52   250.1  883.23     274  901.67   298.3  923.37
   309.3  929.97   320.6  935.24   368.2  944.22   379.6  949.48   391.6  957.56
#Mann= 3 ,-1,0
       0      .1       0  107.58    .045       0  150.29      .1       0
Bank Sta=107.58,150.29
XS Rating Curve= 0 ,0
Exp/Cntr(USF)=0,0
Exp/Cntr=0.3,0.1

Type RM Length L Ch R = 1 ,19935   ,143,144.2,148
XS GIS Cut Line= 3
1636194.10147958452870.4582862221636529.93139012452900.993291019
1636568.73359238452871.343318867
#Sta/Elev= 30
       0  894.89     2.8  892.45    12.7  880.56    19.3  873.37    22.6  870.37
    25.9     868    29.2  866.0232.29765864.6589    35.8  863.78    45.6  863.53
    62.1  863.6275.39452864.7246    88.5  866.14    95.1   868.7    98.4   869.5
   121.4   870.4   131.3  870.23   177.4  871.68   220.2  871.11   256.5  871.75
   315.8  871.67   322.4  872.01     329  873.19   335.2  875.59   343.4  879.86
   355.8  887.94   359.3  889.66   372.3  894.26   380.5   896.7     386  898.88
#Mann= 3 ,-1,0
       0      .1       032.29765    .045       075.39452      .1       0
#XS Ineff= 2 , 0
                          100.06          879.29
Permanent Ineff=
       F       F
Bank Sta=32.29765,75.39452
XS Rating Curve= 0 ,0
Exp/Cntr(USF)=0,0
Exp/Cntr=0.3,0.1

Type RM Length L Ch R = 1 ,19791   ,114.7,156.5,182.2
XS GIS Cut Line= 4
1636087.80106333452869.556710911 1636176.3429153453007.361552762
1636523.61483667453066.5429412911636573.75842725 452922.70829759
#Sta/Elev= 30
       0  869.87    10.3  869.37    45.4  869.84   153.3   873.7   184.7  873.72
   191.3  873.35     198  872.14   204.6  869.72   211.3  865.66216.0002864.1552
   251.2  863.46   264.5  863.63   267.9  864.15   277.8  867.21   281.2  867.66
   304.5  868.77   337.8  868.29   347.7  868.88   410.5  869.58   464.2  871.09
   487.7  872.29   504.2  874.12   516.1  874.49   559.4  874.85   585.4  874.27
   604.4  874.64   616.1  876.36   628.7  880.68     644  884.44   668.4  888.24
#Mann= 3 ,-1,0
       0      .1       0216.0002    .045       0   267.9      .1       0
#XS Ineff= 2 , 0
                          306.03          874.54
Permanent Ineff=
       F       F
Bank Sta=216.0002,267.9
XS Rating Curve= 0 ,0
Exp/Cntr(USF)=0,0
Exp/Cntr=0.3,0.1

Type RM Length L Ch R = 1 ,19635   ,388.7,422.9,445.8
XS GIS Cut Line= 2
 1636163.8736708453022.9665853621636246.18364693453296.140126301
#Sta/Elev= 30
       0  873.13    16.7  872.73    33.8  872.68      51  870.99    54.4  870.52
    64.7  868.28    71.5  867.08    85.2  865.89    88.7  865.17    94.6  863.61
   103.1   862.2   107.8  861.55   113.1  861.22   160.6  861.56     164  861.78
  166.26862.2255   167.5  862.47   171.4  863.82   174.3  865.51   177.7  868.09
   181.2  870.26   189.4  874.66   197.3  878.55   201.7  880.28     212  883.63
   232.6  888.71   239.5  890.25   244.7  891.11   257.9  892.85   285.3  897.38
#Mann= 3 ,-1,0
       0      .1       0   103.1    .045       0  166.26      .1       0
Bank Sta=103.1,166.26
XS Rating Curve= 0 ,0
Exp/Cntr(USF)=0,0
Exp/Cntr=0.3,0.1

Type RM Length L Ch R = 1 ,19212   ,313,302.2,286.8
XS GIS Cut Line= 5
1635954.96049822452775.961876895 1635896.1201361452880.986596256
1635837.01428318452961.6501488391635792.90151051 453022.30553934
1635741.43671842453093.070161596
#Sta/Elev= 30
       0  887.84     8.2  885.33    25.1  881.41    34.5   879.8      42  877.72
    51.6  874.28    64.5  867.05    68.3  866.07    98.4  863.69   120.4  862.65
   125.1  861.73  133.12859.2988   149.9  858.21   163.7  858.43   169.8  858.11
   194.3  858.25  204.87 859.299   220.4  862.72   234.8  868.67   255.1  870.12
   275.4  872.84   279.5  873.58   294.6  877.47   303.8  880.33   307.9  881.12
   328.1  883.14   342.2  883.94   355.9  886.96   361.5  887.69   382.9  888.63
#Mann= 3 ,-1,0
       0      .1       0  133.12    .045       0  204.87      .1       0
Bank Sta=133.12,204.87
XS Rating Curve= 0 ,0
Exp/Cntr(USF)=0,0
Exp/Cntr=0.3,0.1

Type RM Length L Ch R = 1 ,18910   ,319.5,298,272.8
XS GIS Cut Line= 6
1635626.59639692452547.4058985861635623.94581167452634.865697429
1635621.67383459452709.8310986761635614.56295642452809.806620508
1635623.91169101452895.5269215111635642.89852968453018.764535919
#Sta/Elev= 30
       0  992.31    19.1  993.01    25.7  992.11    48.7  986.22    55.2  983.83
    58.5  981.67    81.5  956.31    91.3  948.47   114.7  933.09   117.6  930.46
     134  912.39   147.1  900.48   160.3  889.81   170.1  879.09   183.3  862.88
   186.6  859.63   189.9  857.74  195.21856.0845   199.7  855.23   212.9  854.62
   229.3  854.75   238.1856.0837   258.9  859.84   278.8   860.1   296.5  861.22
   324.9  864.91   381.2  864.83     431  863.01   455.2  864.18   473.6  866.05
#Mann= 3 ,-1,0
       0      .1       0  195.21    .045       0   238.1      .1       0
Bank Sta=195.21,238.1
XS Rating Curve= 0 ,0
Exp/Cntr(USF)=0,0
Exp/Cntr=0.3,0.1

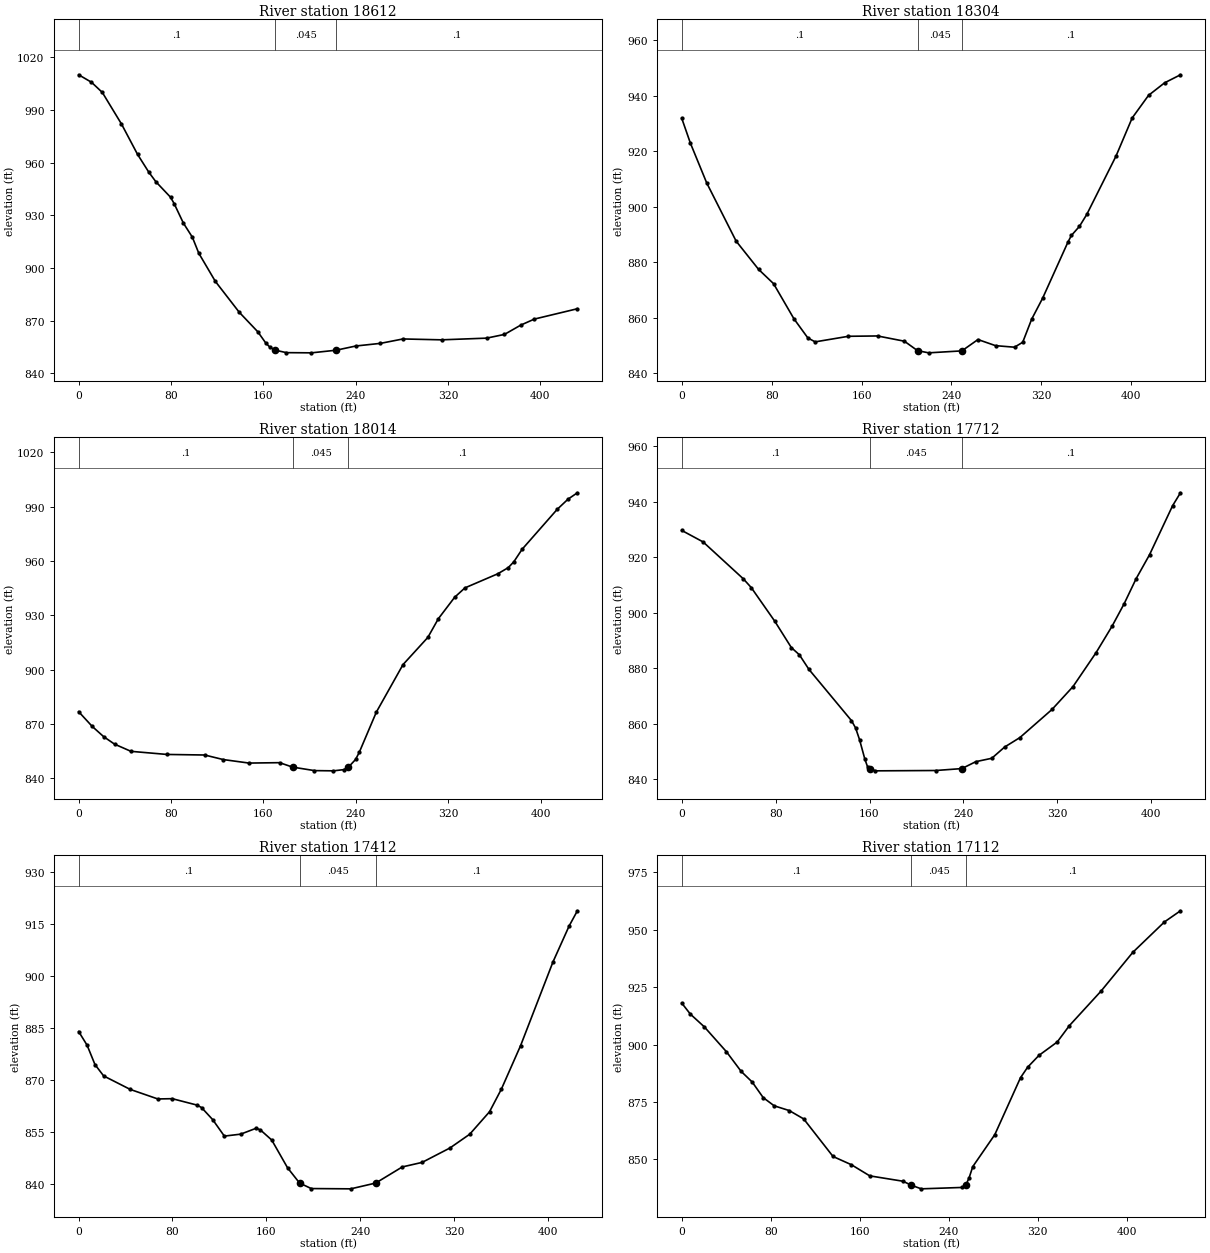
Type RM Length L Ch R = 1 ,18612   ,331,307.5,298.1
XS GIS Cut Line= 6
1635236.04599692452832.8735035061635308.45005159 452882.00496693
1635370.51095109452924.1174155031635453.25816092452980.267565668
1635515.31873234453022.3803423351635588.60205033453082.190918252
#Sta/Elev= 30
       0 1010.09    11.1 1005.83    20.5 1000.03    37.1  982.05      51  964.77
    60.7  954.68    66.9  949.15    79.6  940.34    82.8   936.6    90.7  925.63
    98.5  917.58   104.1   908.4   118.4  892.42   139.1  874.83   155.2  863.69
   162.2  857.21     166  854.74  170.51 853.184     180   851.8   201.7  851.69
  223.02853.1844   240.2  855.59   261.5  857.09     281   859.6   314.4   859.1
   353.4  860.06   368.9  862.18     383  867.47   394.8  870.92   432.1  876.81
#Mann= 3 ,-1,0
       0      .1       0  170.51    .045       0  223.02      .1       0
Bank Sta=170.51,223.02
XS Rating Curve= 0 ,0
Exp/Cntr(USF)=0,0
Exp/Cntr=0.3,0.1

Type RM Length L Ch R = 1 ,18304   ,266.8,290.1,301.4
XS GIS Cut Line= 4
1635159.92828328453153.5852422221635335.59180398 453245.17985345
1635388.33397274 453239.447009021635563.42863212453319.830092842
#Sta/Elev= 30
       0   931.9     7.7  922.94    22.2  908.63    48.4  887.66    68.4  877.48
    81.7  872.35    99.8  859.72   112.2  852.81   118.7  851.39   148.3   853.4
   174.2  853.52   198.1  851.63   209.8  848.23   219.7  847.44  249.26848.1458
   263.6  852.23   279.2  850.03   296.1  849.47   303.4  851.25   311.4  859.58
   321.1  867.09   343.6  887.27   346.7   889.7   353.9  892.99   360.4  897.27
   386.4  918.27   400.8  932.02   415.4  940.18   429.7  944.69   443.8  947.58
#Mann= 3 ,-1,0
       0      .1       0   209.8    .045       0  249.26      .1       0
Bank Sta=209.8,249.26
XS Rating Curve= 0 ,0
Exp/Cntr(USF)=0,0
Exp/Cntr=0.3,0.1

Type RM Length L Ch R = 1 ,18014   ,283,302.3,309.5
XS GIS Cut Line= 6
1635114.25654234453327.1277643441635165.92769884453404.044933334
 1635215.6333081453462.3433731791635291.82541293453527.276970342
1635351.10646234453573.2197918441635420.26806942453626.819750249
#Sta/Elev= 30
       0  876.71    11.7   868.6    21.7  862.89    31.1  858.78    45.3  854.82
    76.5   853.1   109.1  852.79   125.2  850.28   147.5  848.34     174  848.56
  185.27846.1075   204.2  844.18   220.6  844.05   229.7  844.72  233.63846.1088
   239.8  850.32     243  854.26   257.8  876.48   280.9  902.72   302.4  917.73
   311.5  928.05   325.6  939.88   334.5  945.06     363  952.86     372  956.24
   376.8  959.42     384  966.36   414.4  988.42   423.8  994.06   431.9  997.58
#Mann= 3 ,-1,0
       0      .1       0  185.27    .045       0  233.63      .1       0
Bank Sta=185.27,233.63
XS Rating Curve= 0 ,0
Exp/Cntr(USF)=0,0
Exp/Cntr=0.3,0.1

Type RM Length L Ch R = 1 ,17712   ,299.6,299.3,301.8
XS GIS Cut Line= 6
1634908.81338367453372.5098914211634933.25460775453456.527111843
1634954.20436901453528.5417315961634982.13738401453624.561224595
1635003.08714525453696.5758443331635027.52836934453780.593064755
#Sta/Elev= 30
       0  929.69    18.2  925.54    52.4  912.26    59.2  909.09    79.3  896.92
    93.4  887.43   100.2  884.85   108.4  879.56   144.6  861.11   148.1  858.48
   151.5  854.24     156  847.24   158.3  844.47     160843.7957   165.1  842.98
   216.4   843.1  238.72843.7955   250.6  846.29   264.2  847.51   275.1  851.55
   288.1  854.96   315.5  865.11   333.4  873.36   353.1  885.63   366.7  895.15
     377  903.25   387.2  912.28   398.6   920.9   418.3  938.62     425  943.27
#Mann= 3 ,-1,0
       0      .1       0     160    .045       0  238.72      .1       0
Bank Sta=160,238.72
XS Rating Curve= 0 ,0
Exp/Cntr(USF)=0,0
Exp/Cntr=0.3,0.1

Type RM Length L Ch R = 1 ,17412   ,295.4,300.7,315.1
XS GIS Cut Line= 6
1634636.89069918453451.8371605871634654.24073009453537.692631915
1634669.41360001453611.2075767521634692.36270109453708.547933251
1634710.55262534453781.3086145071634731.77436768453866.196240008
#Sta/Elev= 30
       0   884.1     7.2  880.14    13.9  874.57    21.3  871.29      44  867.39
    67.5  864.64    79.8  864.72   100.9  862.87   104.8  862.15   114.3  858.66
   124.2  853.92   138.1  854.48   151.2  856.17   154.8  855.75   164.6  852.79
   178.1  844.77  188.34840.3729   198.3  838.78     232   838.7  253.28840.3729
   275.9  845.02   292.8  846.33   316.5  850.48   333.4  854.46   350.3  860.95
   360.4  867.48   376.8  880.05   404.4   904.2   418.2  914.59   425.2  918.95
#Mann= 3 ,-1,0
       0      .1       0  188.34    .045       0  253.28      .1       0
Bank Sta=188.34,253.28
XS Rating Curve= 0 ,0
Exp/Cntr(USF)=0,0
Exp/Cntr=0.3,0.1

Type RM Length L Ch R = 1 ,17112   ,307.4,298.9,288.8
XS GIS Cut Line= 6
1634407.12639493453458.404076591 1634396.5972165453545.268404171
1634387.57262826453619.7233077591634375.53951584453718.996731251
 1634366.5145995453793.4519629181634430.19032517453884.167004585
#Sta/Elev= 30
       0  918.05     7.7  913.27    20.3  907.69    40.2  896.84    53.4   888.3
    63.3  883.68    73.2  876.88    83.1   873.3    96.6  871.24   109.6   867.6
     136  851.23   152.5  847.64     169  842.79   198.8  840.46  206.42  838.71
   215.3  837.14   251.7  837.74  255.26838.7087   258.3  841.94   261.6  846.82
   281.4  860.75   304.5  885.55   310.9  890.11   321.1  895.28   337.5   901.1
   348.4  908.21     377  923.33   405.5  940.18   433.9  953.41   448.3  958.26
#Mann= 3 ,-1,0
       0      .1       0  206.42    .045       0  255.26      .1       0
Bank Sta=206.42,255.26
XS Rating Curve= 0 ,0
Exp/Cntr(USF)=0,0
Exp/Cntr=0.3,0.1

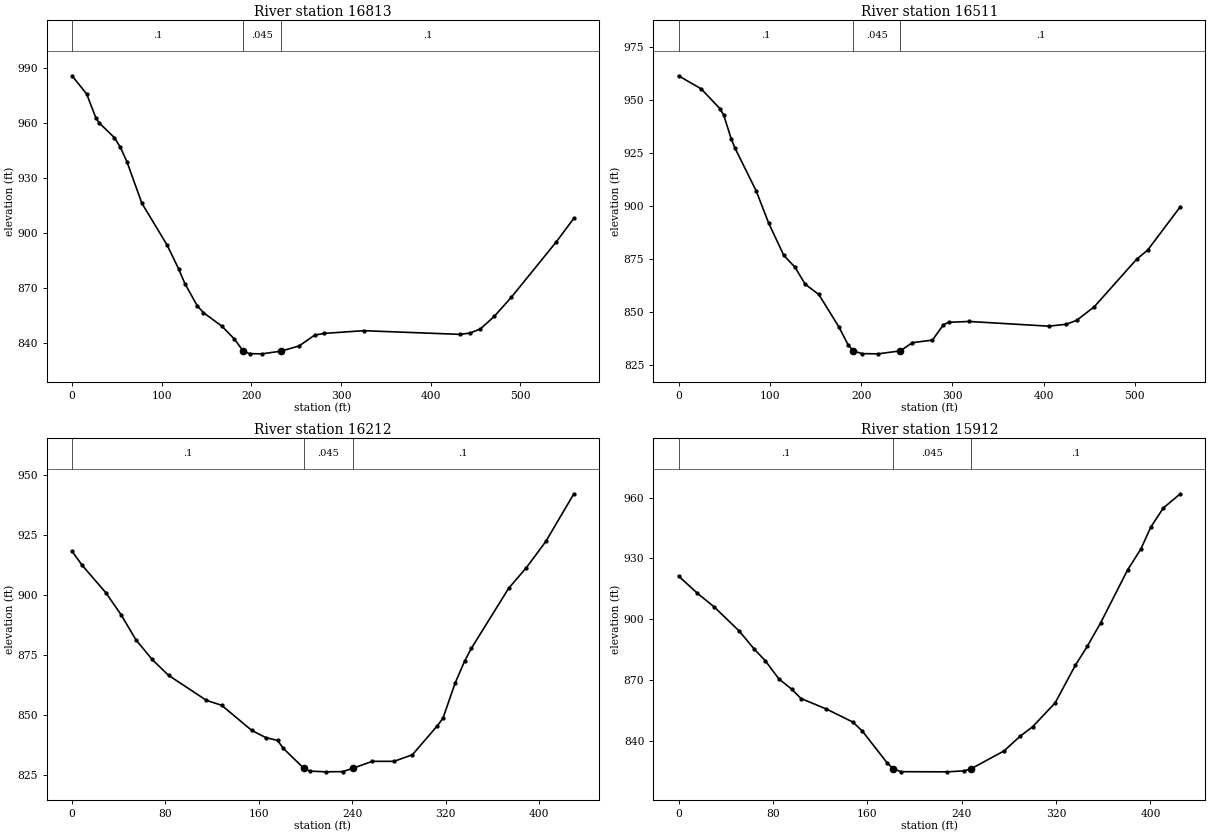
Type RM Length L Ch R = 1 ,16813   ,338.7,302,250.8
XS GIS Cut Line= 6
1634023.30137518 453459.725268171634048.54935618453543.503643915
1634070.19038901453615.3135396691634111.29914503 453741.69463448
1634180.36077234 453783.593058751634337.11341159453879.237552509
#Sta/Elev= 30
       0  985.64    16.3   975.7    26.5  962.77      30  960.09    47.1  951.98
      54  946.55    61.3  938.64    77.9  916.12     106  893.37   119.1  880.13
   125.9  872.32   139.6  860.27   146.5  856.51   167.1  849.15   180.9  842.22
  191.02835.5085   198.1  834.16   211.9  834.05  232.96835.5083   253.3  838.35
   270.6  844.24   280.9  845.18   325.3  846.67   432.5  844.67     444  845.37
   455.5  847.64   470.9  854.41     490  864.87   540.1  895.03   559.8  907.95
#Mann= 3 ,-1,0
       0      .1       0  191.02    .045       0  232.96      .1       0
Bank Sta=191.02,232.96
XS Rating Curve= 0 ,0
Exp/Cntr(USF)=0,0
Exp/Cntr=0.3,0.1

Type RM Length L Ch R = 1 ,16511   ,300.6,299.1,296.8
XS GIS Cut Line= 6
1633867.45523018454020.7487524151633937.25003809453967.976548254
1633997.07439351453922.7430429161634121.50518089453832.282802589
1634198.29048353453834.7130716181634331.56224158453917.080652669
#Sta/Elev= 30
       0  961.39    24.8  955.23    45.4  945.88    49.5  942.85    57.7  931.68
    61.8  927.32      85  907.17    98.8  891.84   115.4  876.63   127.6   871.1
   138.8  863.06   153.7  858.23   175.8  842.85   185.8  834.47  191.48 831.632
   201.1  830.32   218.6  830.23  243.07831.6331   256.2  835.51   278.2   836.7
   290.3  844.01   296.1   845.1   318.3   845.5   405.5  843.29   424.7  844.16
   436.3  846.04   455.6  852.47   501.9  874.85   513.9   879.1   549.8  899.63
#Mann= 3 ,-1,0
       0      .1       0  191.48    .045       0  243.07      .1       0
Bank Sta=191.48,243.07
XS Rating Curve= 0 ,0
Exp/Cntr(USF)=0,0
Exp/Cntr=0.3,0.1

Type RM Length L Ch R = 1 ,16212   ,299,300,302.8
XS GIS Cut Line= 6
1634065.17169826454261.7453176681634131.84741792454205.083029419
1634189.05432451454156.5821421741634265.33041868454091.913636342
1634322.53699717454043.4124210031634408.20185208454009.147397667
#Sta/Elev= 30
       0  918.13     8.7  912.25    28.9   900.9      42  891.71    54.6  881.37
    68.6  873.12    82.6  866.54   115.1  856.11   128.1  854.08   153.9  843.61
   165.8  840.66     176  839.44     181  836.13  198.54827.8356   203.6   826.7
   217.6  826.39   231.8  826.49  240.27827.8377   257.1  830.75   275.8  830.77
   291.5  833.48     313  845.63   317.7  848.73   328.2  863.41   336.3  872.49
   342.1  877.84     374  902.76   389.2  911.35   405.8  922.21   429.8  942.03
#Mann= 3 ,-1,0
       0      .1       0  198.54    .045       0  240.27      .1       0
Bank Sta=198.54,240.27
XS Rating Curve= 0 ,0
Exp/Cntr(USF)=0,0
Exp/Cntr=0.3,0.1

Type RM Length L Ch R = 1 ,15912   ,301.2,301.7,299.3
XS GIS Cut Line= 6
1634228.47616167 454488.440074251634300.31263217454438.482497007
1634361.88698409454395.6620445851634443.98590125454338.567670584
1634504.75612092454294.590724424  1634572.496471454238.742739007
#Sta/Elev= 30
       0  921.34      16  912.85    30.2  906.12    51.4  894.24    63.9  885.48
    73.6  879.51    85.1  870.57    95.9  865.55   103.8  860.93   125.3  855.75
   147.8  849.28   155.8  844.86     177  829.04  182.03826.3116   188.5  824.83
   227.7  824.76   242.3  825.26  248.11826.3116   275.9  835.09   289.3  842.21
   300.2  847.05   319.2  858.78   336.3   877.3   346.4  886.63   357.8   898.3
   380.6  924.34   391.8  934.62   400.3  945.51   410.9  954.91   425.3  961.92
#Mann= 3 ,-1,0
       0      .1       0  182.03    .045       0  248.11      .1       0
Bank Sta=182.03,248.11
XS Rating Curve= 0 ,0
Exp/Cntr(USF)=0,0
Exp/Cntr=0.3,0.1