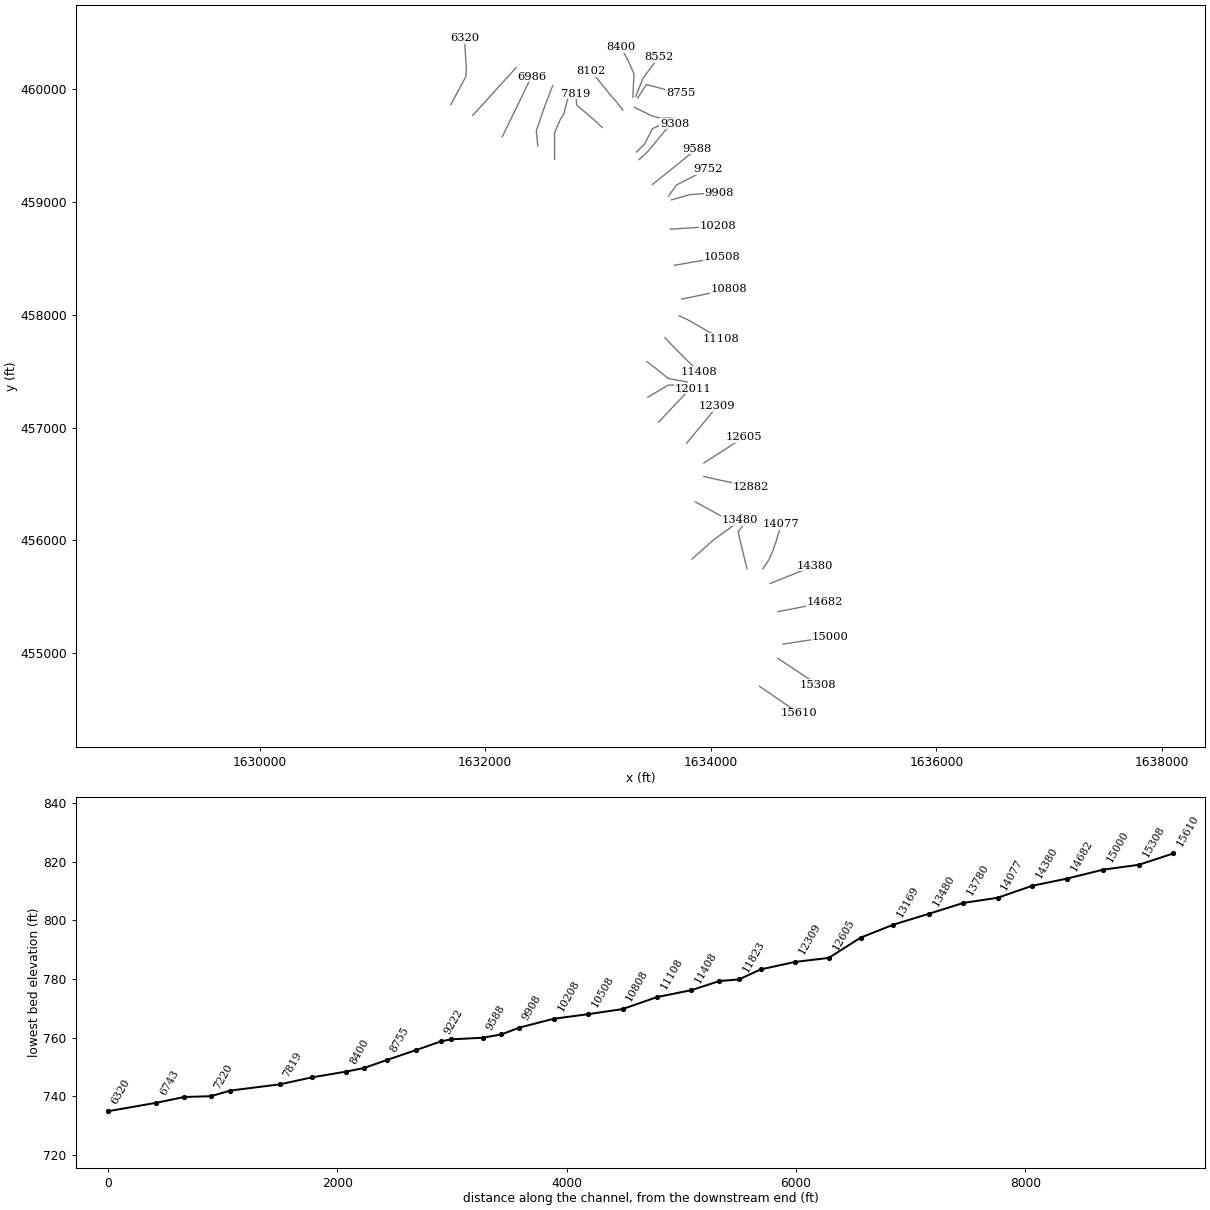
HEC-RAS study LynCmpRn.prj: LynCmpRn

--- LynCmpRn.g01 (geometry) --- (continued)

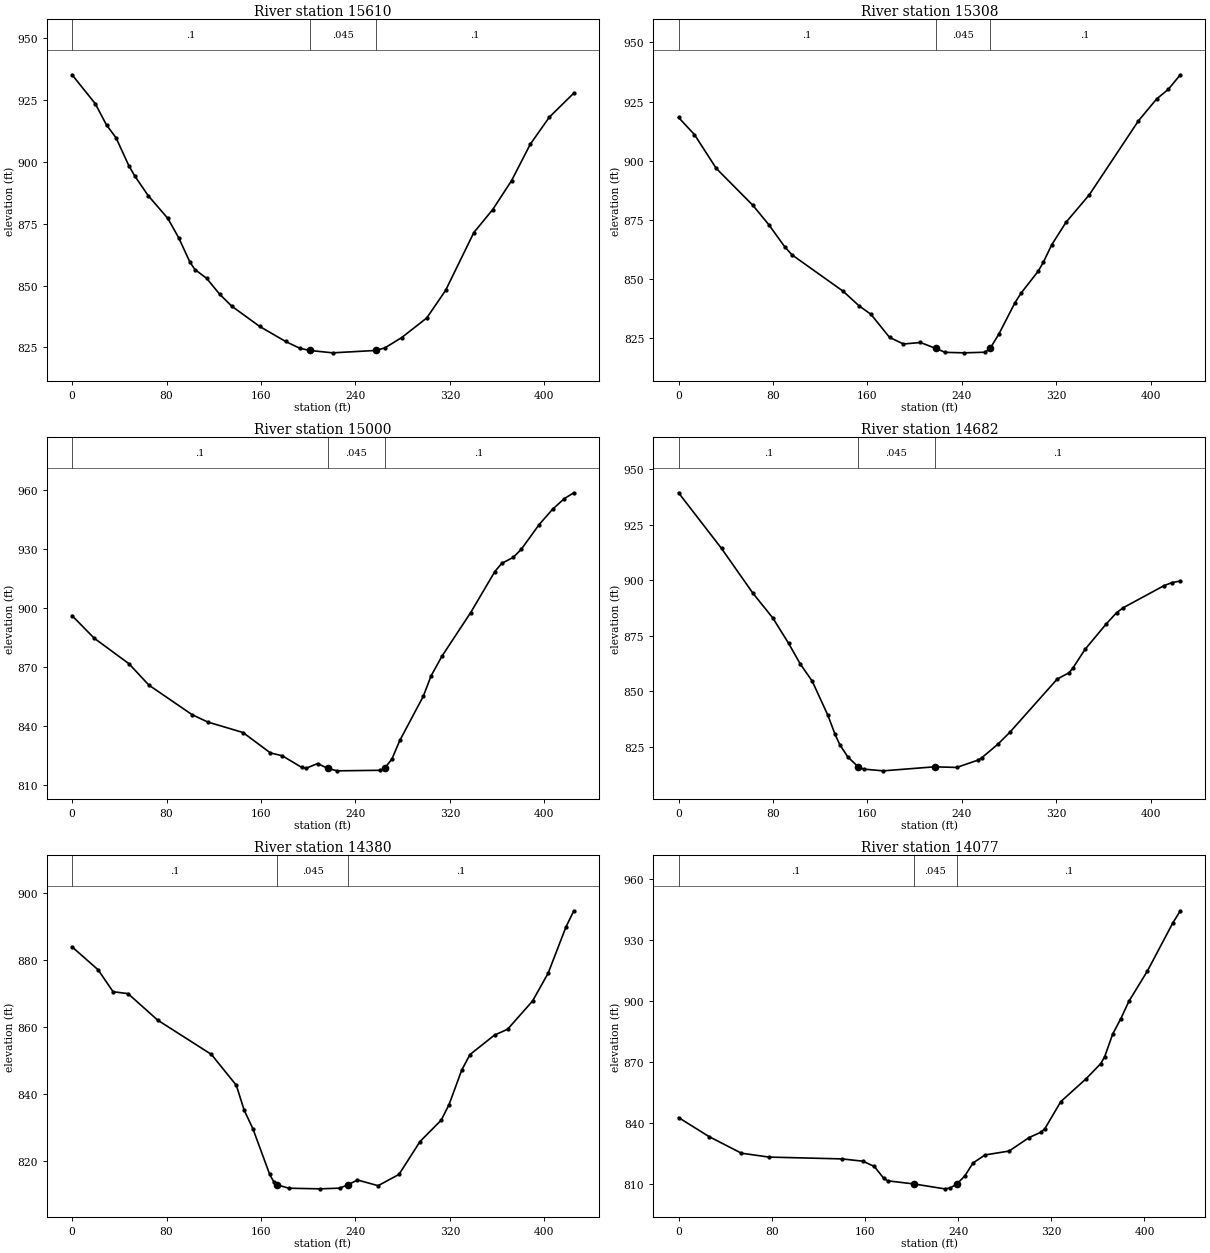
Type RM Length L Ch R = 1 ,15610   ,301.8,302.1,302.4
XS GIS Cut Line= 6
1634430.74478601454705.7227761751634502.73381525454655.985342845
1634564.43841626454613.3528821771634646.71154568454556.509819999
1634708.41647476454513.877359346  1634780.405504454464.139597923
#Sta/Elev= 30
       0   935.2    19.7  923.49    29.2  914.86    37.2  909.77      48  898.53
    53.2  894.21    64.5  886.34    81.1  877.16    90.5  869.14    99.9  859.37
   104.1  856.48   114.1  852.86   124.9  846.56   135.3  841.65   158.9  833.48
   180.8  827.42   192.7   824.7  201.13823.7814   220.7  822.81  257.33823.7815
     265  824.82   279.2  828.99   300.4   836.9   316.4  848.08   340.3  871.44
   356.2  880.68   372.2  892.38   388.1  907.14   404.2  918.06     425   927.8
#Mann= 3 ,-1,0
       0      .1       0  201.13    .045       0  257.33      .1       0
Bank Sta=201.13,257.33
XS Rating Curve= 0 ,0
Exp/Cntr(USF)=0,0
Exp/Cntr=0.3,0.1

Type RM Length L Ch R = 1 ,15308   ,292.1,307.8,326.3
XS GIS Cut Line= 6
  1634594.449183454951.9650658371634667.43000817454903.694493085
 1634729.9846731454862.3195758461634813.39133042454807.153019503
1634875.94632342454765.778102249 1634948.9271486454717.507201418
#Sta/Elev= 30
       0  918.31    13.5  911.07      32  896.77    62.8   881.3    76.5  873.01
    89.8  863.79    96.1  860.29   139.4  844.94   152.8  838.81     163  835.17
   178.7  825.46   190.5  822.65   204.9  823.29  217.94820.7568   225.9  819.13
   241.7  818.92   259.3  819.17  263.84820.7582   271.2  826.73   284.9  840.04
   290.1  844.13   304.6  853.38     309  857.19   316.1  864.58   328.2  874.06
   347.9  885.65   389.5  916.87   404.9  926.11   414.7  930.12     425  936.33
#Mann= 3 ,-1,0
       0      .1       0  217.94    .045       0  263.84      .1       0
Bank Sta=217.94,263.84
XS Rating Curve= 0 ,0
Exp/Cntr(USF)=0,0
Exp/Cntr=0.3,0.1

Type RM Length L Ch R = 1 ,15000   ,315.2,317.6,312.3
XS GIS Cut Line= 6
1634639.75945984455078.5304295121634726.24222651455091.835521013
1634800.37003101455103.2396976651634899.20710367 455118.44504784
1634973.33490817455129.8492245081635059.81767485455143.154316008
#Sta/Elev= 30
       0  896.12    18.7  884.67    48.2  871.68    65.1  860.81   101.7   845.8
   114.9  842.09   144.8  836.75     168  826.38     178  824.95   194.6     819
   198.4  818.65   207.9  820.98  216.54818.5671   224.5  817.29     261  817.57
  264.65818.5659   270.9  823.27   277.6  832.74   297.5   855.2   304.1  865.56
   313.4  875.64   337.5  897.56   358.1  918.52   363.9  922.65   373.8  925.77
   380.5  929.84   395.5  942.29     407  950.16     417  955.59     425  958.51
#Mann= 3 ,-1,0
       0      .1       0  216.54    .045       0  264.65      .1       0
Bank Sta=216.54,264.65
XS Rating Curve= 0 ,0
Exp/Cntr(USF)=0,0
Exp/Cntr=0.3,0.1

Type RM Length L Ch R = 1 ,14682   ,293.9,302.7,304.8
XS GIS Cut Line= 6
1634596.26217151 455366.826768921634682.25675017455383.350685999
1634755.93672092 455397.643636421634853.94111809455417.621614844
1634927.28906851455433.2410061661635012.80956675455451.720299929
#Sta/Elev= 30
       0  939.42    36.4  914.37    63.1  894.13    79.8   883.1    93.2  871.67
   103.2  862.27   113.2  854.65   126.6  839.14   132.6  830.64   136.6  826.01
   143.3  820.58  152.21815.9963   156.7     815   173.4  814.22   216.9  816.03
   235.7  815.75   253.7  819.06   257.1   820.2   270.5   826.2   280.6  831.54
   320.8  855.55   330.9   858.4   334.2  860.59   344.3  868.86   362.3  880.35
   371.1  885.43   376.8  887.68   411.4  897.63   418.1  898.99   425.1  899.69
#Mann= 3 ,-1,0
       0      .1       0  152.21    .045       0   216.9      .1       0
Bank Sta=152.21,216.9
XS Rating Curve= 0 ,0
Exp/Cntr(USF)=0,0
Exp/Cntr=0.3,0.1

Type RM Length L Ch R = 1 ,14380   ,285.6,303.1,319.9
XS GIS Cut Line= 6
1634525.77576393455616.3735139221634607.01772742455648.870496169
1634676.65341492455676.7244430931634769.50099826455713.863476425
1634839.13701384455741.7177514281634920.37864925455774.214405596
#Sta/Elev= 30
       0  884.06    22.1  877.19    34.7  870.66    47.4  870.08    72.6  862.14
     118  851.93   139.1  842.72   145.8  835.24   153.2  829.69   167.4  816.07
     171  813.76  173.71812.9825   183.6  811.97   209.8  811.78   226.6  811.98
  233.74  812.98   241.7  814.43   259.2  812.72   276.9  816.09   294.7  825.91
   312.7  832.32   319.3  836.95     330  847.23     337  851.88   357.8  857.71
   368.8  859.42     390  867.87   403.2  876.18   418.4  890.08     425  894.83
#Mann= 3 ,-1,0
       0      .1       0  173.71    .045       0  233.74      .1       0
Bank Sta=173.71,233.74
XS Rating Curve= 0 ,0
Exp/Cntr(USF)=0,0
Exp/Cntr=0.3,0.1

Type RM Length L Ch R = 1 ,14077   ,283.1,296.9,307.5
XS GIS Cut Line= 6
1634461.42877975455746.7049461751634512.78169543455823.387863666
1634544.41286576 455892.310626091634578.21233884455986.632287845
1634599.06662785456058.6744665951634625.29951501456142.147724837
#Sta/Elev= 30
       0  842.68    26.3  833.29      54  825.17    77.7  823.26   140.3  822.37
   158.3  821.24   168.1  818.65   176.1  812.88   179.6   811.6   202.2810.0638
   228.4  807.67   233.2  808.08  238.96810.0627   245.8  814.02   252.8  820.36
   263.2  824.32   283.8  826.22   300.9  832.84   311.1  835.46   314.6  837.29
   328.2  850.51   350.1  861.82   362.5  869.18   365.9  872.63   372.8  883.77
   379.7  891.19   386.6  899.72   402.5  914.59   424.4  938.27   430.8   944.2
#Mann= 3 ,-1,0
       0      .1       0   202.2    .045       0  238.96      .1       0
Bank Sta=202.2,238.96
XS Rating Curve= 0 ,0
Exp/Cntr(USF)=0,0
Exp/Cntr=0.3,0.1

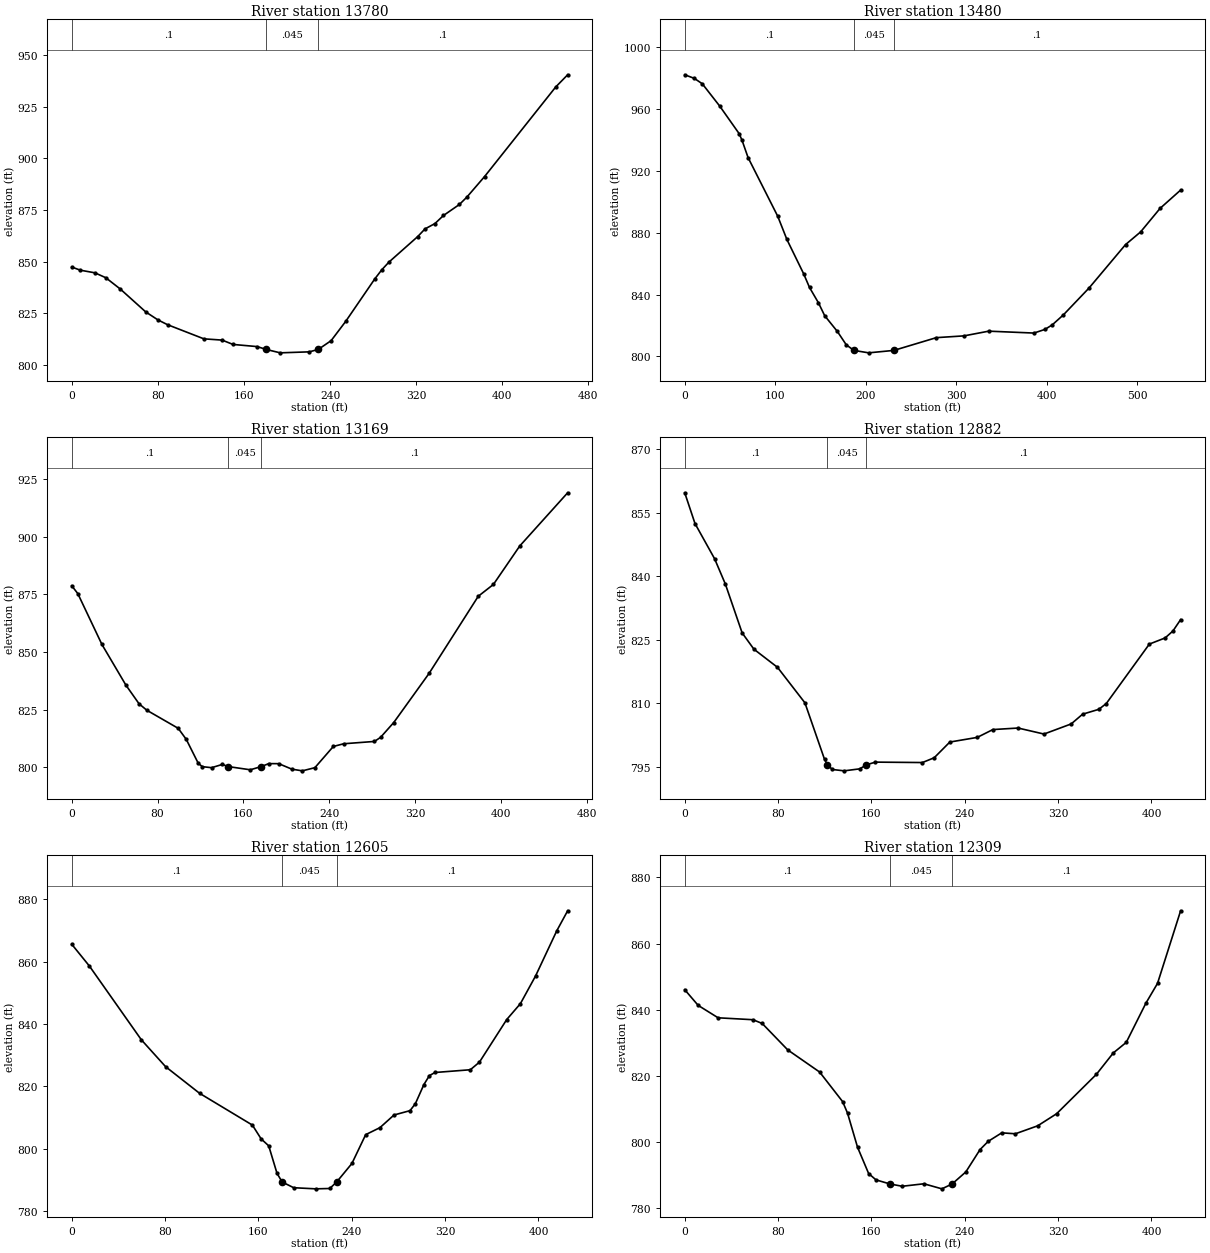
Type RM Length L Ch R = 1 ,13780   ,328.1,300,279.5
XS GIS Cut Line= 6
1634320.71318193455747.7354559151634299.97962759455832.743487999
1634282.20800959455905.6075154991634258.51284701456002.759552166
1634243.39148617456076.2699038391634317.98680942456174.378959596
#Sta/Elev= 30
       0  847.47     7.9  845.94    21.5  844.66    31.6  842.29    45.1  836.81
    68.7  825.75      80  821.89      89  819.55   122.8   812.7   139.7   812.1
   149.8     810   172.3  808.95  180.65807.5743   193.7  805.93   220.7  806.41
  229.04807.5747     241  811.83   254.5  821.12   281.5  841.66     288  846.08
   294.7  849.84   321.5  862.22   328.2   865.9   337.5  868.51   345.4  872.41
   360.2  877.74   367.2  881.34   383.6  891.26   449.7  934.61   460.8  940.52
#Mann= 3 ,-1,0
       0      .1       0  180.65    .045       0  229.04      .1       0
Bank Sta=180.65,229.04
XS Rating Curve= 0 ,0
Exp/Cntr(USF)=0,0
Exp/Cntr=0.3,0.1

Type RM Length L Ch R = 1 ,13480   ,337.5,311,288.9
XS GIS Cut Line= 6
1633833.35949785455833.639483586  1633898.757661455891.771257088
1633954.81365126455941.5985852631634029.55431542 456008.03513217
1634128.91205634456078.9076938331634260.74742259456175.697854593
#Sta/Elev= 30
       0  982.31    10.6  979.98    19.4  976.48    38.6  962.08    60.1  944.22
    63.3  939.94      70  928.69   102.8  890.67   112.9  875.67   131.5  853.35
   137.9  844.58   147.8  834.61   154.7  826.27   168.7  816.07   178.6  807.38
  187.02803.8062   203.3  802.23  231.13803.8064   278.1  812.07   308.7  813.22
     336  816.27   385.9  815.04   398.1  817.39   406.3  820.39   418.5   826.8
     447  844.29   487.2  872.32   503.9  880.56   525.4  895.79   548.1  907.64
#Mann= 3 ,-1,0
       0      .1       0  187.02    .045       0  231.13      .1       0
Bank Sta=187.02,231.13
XS Rating Curve= 0 ,0
Exp/Cntr(USF)=0,0
Exp/Cntr=0.3,0.1

Type RM Length L Ch R = 1 ,13169   ,281.1,286.4,290.1
XS GIS Cut Line= 6
1633862.65340251456340.986894086 1633939.2989185 456298.77667667
1634004.99498133456262.596302837 1634092.5899505456214.355585679
1634160.42970984456182.0679205951634276.50624934456227.278132007
#Sta/Elev= 30
       0  878.71     5.6  875.35    28.1  853.29    50.5  835.63    62.7  827.58
    69.9  824.79    99.2  816.94   106.7  812.16   117.9  801.77   121.7  800.32
   130.3  799.88   140.4   801.3  145.57  800.37   166.4  798.97  176.68  800.37
   183.6  801.64   192.9  801.62   205.2  799.23   214.9  798.51   226.6  799.88
   243.8  809.08   253.5  810.25   282.1  811.25   287.8  813.02   300.1  819.45
     333  840.72   378.9  874.19     393   879.3   417.6     896   462.2  919.03
#Mann= 3 ,-1,0
       0      .1       0  145.57    .045       0  176.68      .1       0
Bank Sta=145.57,176.68
XS Rating Curve= 0 ,0
Exp/Cntr(USF)=0,0
Exp/Cntr=0.3,0.1

Type RM Length L Ch R = 1 ,12882   ,258.3,277.1,295
XS GIS Cut Line= 6
1633937.68802933456566.0602628441634023.03497151 456546.73517026
1634096.28646542456530.6272628461634194.09696534   456509.816937
1634267.45508634456494.2087005081634353.03923276456475.999419332
#Sta/Elev= 30
       0  859.74     8.8  852.47    25.6  844.15    34.8  838.19    49.2  826.64
    59.3  822.79    79.5  818.51     103  810.13   119.8  796.78  122.35795.4789
   126.5  794.38   136.6  794.06     150  794.53  155.71 795.476   163.4  796.12
   203.7  796.02   213.8  797.15   227.2  800.86   250.7  801.96   264.1  803.81
   285.7  804.17   307.9  802.75   331.2  805.14     341  807.44   354.9  808.59
   361.3  809.96   398.2     824   411.7  825.45   418.4  827.09     425  829.78
#Mann= 3 ,-1,0
       0      .1       0  122.35    .045       0  155.71      .1       0
Bank Sta=122.35,155.71
XS Rating Curve= 0 ,0
Exp/Cntr(USF)=0,0
Exp/Cntr=0.3,0.1

Type RM Length L Ch R = 1 ,12605   ,288.8,296,303.9
XS GIS Cut Line= 3
1633937.68015534456685.6377795931634221.71337992456867.934002921
1634295.23980768456915.369603589
#Sta/Elev= 30
       0  865.54    15.1  858.57    59.6  834.94    80.4  826.32   109.5  817.79
   154.8  807.59   162.3  803.17   168.8  800.94   175.9  792.13180.3377789.3449
   190.2  787.52     209  787.16   221.1  787.27227.0076789.3477   240.1  795.29
   251.9  804.53   264.1  806.77   276.2  810.83   289.9  812.22   294.5  814.47
   301.8  820.59   306.5  823.45   311.3  824.45   341.6  825.33   349.4  827.77
   372.8  841.43   384.5  846.51   397.5  855.39   415.7  869.89     425  876.28
#Mann= 3 ,-1,0
       0      .1       0180.3377    .045       0227.0076      .1       0
Bank Sta=180.3377,227.0076
XS Rating Curve= 0 ,0
Exp/Cntr(USF)=0,0
Exp/Cntr=0.3,0.1

Type RM Length L Ch R = 1 ,12309   ,298.6,297.6,296.7
XS GIS Cut Line= 6
1633785.74935684456862.0488440841633841.67214526456929.345625505
1633889.60610451456987.0285810081633953.51805018457063.939844504
1634001.45200942457121.6228000071634057.37479784457188.919581428
#Sta/Elev= 30
       0  846.03    11.5  841.29    28.6  837.53    58.5  836.95    66.4  835.81
    88.3  827.81   115.6  821.12   135.3  812.18   139.5  808.71   148.1  798.37
   157.6  790.42   163.9  788.49   176.2  787.23   186.4  786.56     205  787.31
   220.4  785.78   229.1  787.24   240.9  790.89   253.1  797.66   260.1  800.15
   271.7  802.72   283.4  802.44   302.5  804.85   318.7   808.5   352.8  820.42
   367.3   826.9   378.4  830.09   395.2  841.93   405.2  847.94     425  869.91
#Mann= 3 ,-1,0
       0      .1       0   176.2    .045       0   229.1      .1       0
Bank Sta=176.2,229.1
XS Rating Curve= 0 ,0
Exp/Cntr(USF)=0,0
Exp/Cntr=0.3,0.1

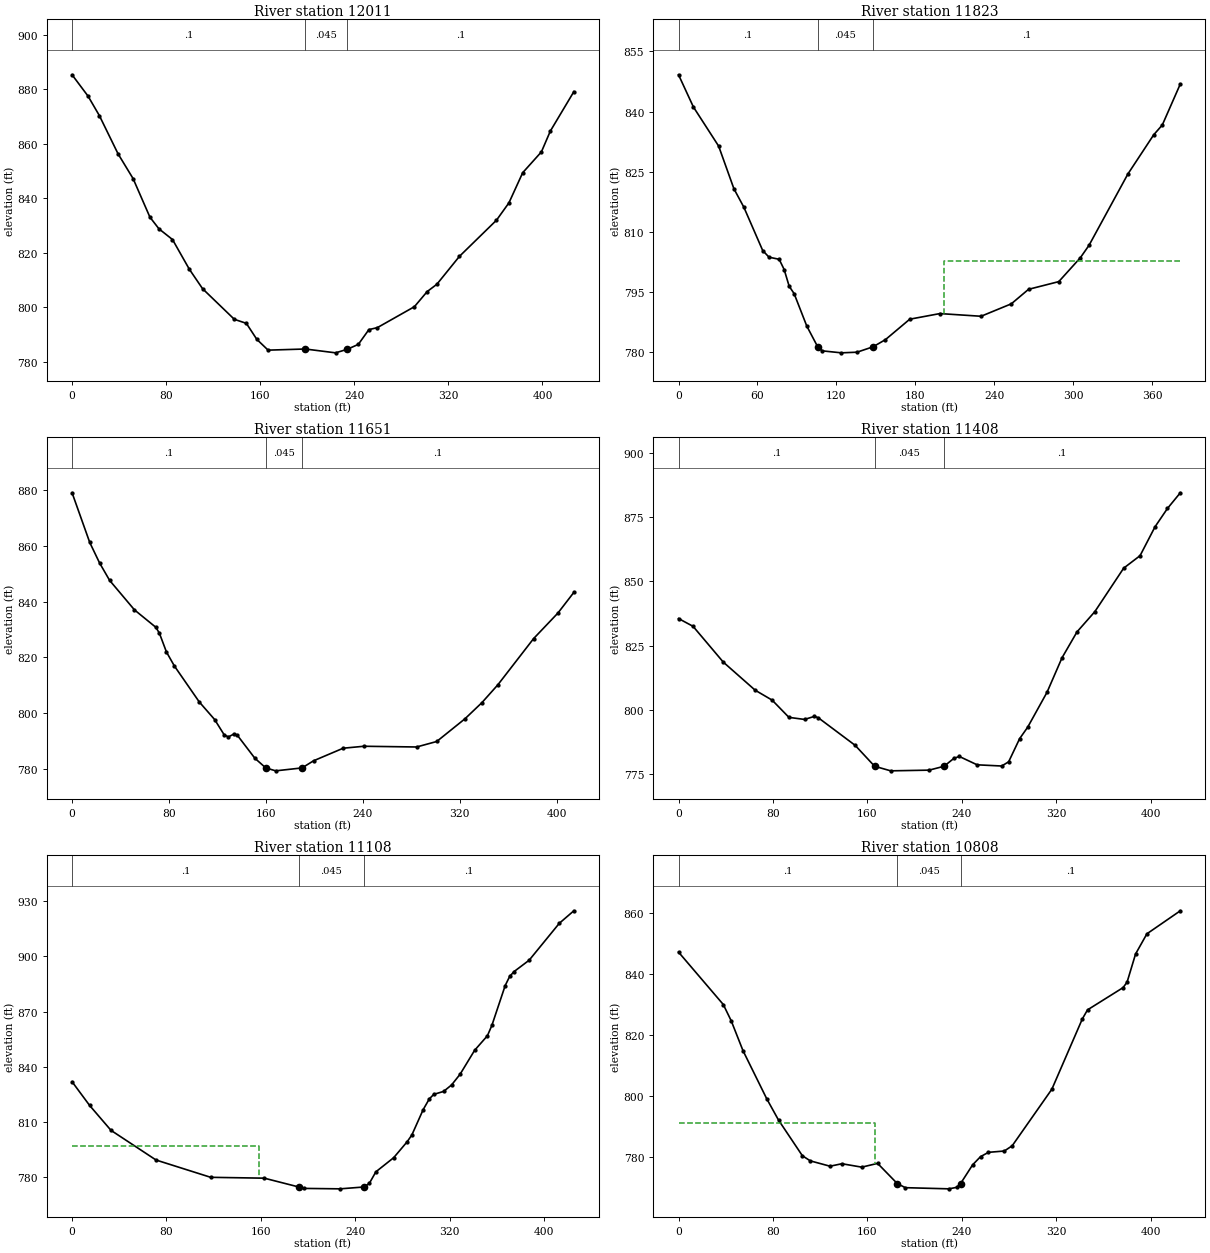
Type RM Length L Ch R = 1 ,12011   ,193.8,188.9,182.1
XS GIS Cut Line= 6
1633536.67898884457048.0970284191633596.68641476457111.778659582
1633648.12135126457166.3628680111633716.70126659457239.141921923
1633768.13653117457293.7261303371633840.88736993457345.399255335
#Sta/Elev= 30
       0   885.4    13.6  877.55    23.2  870.41    39.1  856.36    51.9  847.25
    66.2  833.09    73.9  828.79    85.4  824.87    99.7  813.97     111  806.79
     138  795.55   148.2  794.08   157.1   788.2   166.7  784.23   198.3  784.65
   224.1  783.24   234.1  784.56   243.4  786.34   252.4  791.77   259.6   792.5
   291.1  800.19     302  805.76   310.2  808.43   329.4  818.69   360.9  831.97
   371.5  838.35   383.2  849.42   399.1  857.07   406.7  864.72   426.7   879.2
#Mann= 3 ,-1,0
       0      .1       0   198.3    .045       0   234.1      .1       0
Bank Sta=198.3,234.1
XS Rating Curve= 0 ,0
Exp/Cntr(USF)=0,0
Exp/Cntr=0.3,0.1

Type RM Length L Ch R = 1 ,11823   ,189.7,171.2,143.2
XS GIS Cut Line= 3
1633440.96803562457268.8719416161633622.49522032457377.137033835
1633792.62607952457378.765080334
#Sta/Elev= 30
       0  849.17    11.3  841.14    30.5  831.38    42.1  820.75    49.7  816.12
      64  805.34    68.8  803.68    76.5  803.16    80.3  800.61    84.1  796.45
    87.9  794.58    97.5  786.51  105.77  781.35   109.4  780.32   123.8  779.83
   135.7  779.99   147.9781.3391   157.3  783.12   175.8  788.22   198.7  789.62
     230  788.95     253  792.05   266.1  795.67   289.1  797.59   305.5  803.55
   312.1  806.65   341.6  824.41   361.3  834.22   367.8  836.65   381.5  846.88
#Mann= 3 ,-1,0
       0      .1       0  105.77    .045       0   147.9      .1       0
#XS Ineff= 2 , 0
                          201.55          802.77
Permanent Ineff=
       F       F
Bank Sta=105.77,147.9
XS Rating Curve= 0 ,0
Exp/Cntr(USF)=0,0
Exp/Cntr=0.3,0.1

Type RM Length L Ch R = 1 ,11651   ,244,243.5,241.1
XS GIS Cut Line= 4
1633432.75015327457585.2213705861633539.53466811457504.466934267
1633621.87331276457435.2742307461633791.96259901457404.898480177
#Sta/Elev= 30
       0  879.05    14.6  861.21    22.7  853.87      31  847.61    51.5  837.03
    69.2  830.76    72.1  828.64    77.9  821.93    84.4  816.93     105  803.99
   117.7  797.67   125.6  792.17     129  791.44   133.8  792.53   136.4  792.05
   150.9  783.78   159.9  780.32   168.1  779.27  189.84  780.32   199.3  782.87
   223.8  787.39   240.9  788.09   284.4  787.83     301   789.8   324.4  797.98
   338.3  803.74   351.4  810.11     381  826.74     401  835.87   414.2  843.31
#Mann= 3 ,-1,0
       0      .1       0   159.9    .045       0  189.84      .1       0
Bank Sta=159.9,189.84
XS Rating Curve= 0 ,0
Exp/Cntr(USF)=0,0
Exp/Cntr=0.3,0.1

Type RM Length L Ch R = 1 ,11408   ,289.9,300,305.1
XS GIS Cut Line= 6
1633593.37408543457797.4606871751633653.40546143457733.748544261
1633706.03823018 457680.315252171633776.74904676457609.604435593
1633829.78174908457556.5714051721633891.65367259457494.699481666
#Sta/Elev= 30
       0  835.54    12.3   832.5    37.9  818.55    64.9   807.6    79.3  803.72
    93.5  797.01   106.7   796.2   115.1  797.39   118.3  796.88   149.6   786.1
  166.09777.9401   179.7  776.16   212.2  776.43  224.88777.9395   233.2  781.02
   237.8  781.77   252.9  778.51   273.7  778.04   279.6  779.69   288.9  788.71
   295.7  793.16   312.1  806.79   324.8  820.24   337.5  830.34   352.6  838.23
     377  855.17   390.9  860.05   403.6  871.33   414.1  878.46     425  884.57
#Mann= 3 ,-1,0
       0      .1       0  166.09    .045       0  224.88      .1       0
Bank Sta=166.09,224.88
XS Rating Curve= 0 ,0
Exp/Cntr(USF)=0,0
Exp/Cntr=0.3,0.1

Type RM Length L Ch R = 1 ,11108   ,281.6,300,321.3
XS GIS Cut Line= 6
  1633719.506051457992.0433032511633799.12564242457954.993180498
1633864.18752018457917.6848561761633950.93734667457867.940205008
1634015.99922442457830.631880671 1634091.9052406457787.105392918
#Sta/Elev= 30
       0  831.92    14.9  819.03      33  805.53    71.2  789.43   117.5  780.05
   162.9  779.59  192.15774.8072   196.9  774.03   227.2   773.8   247.4774.8066
   251.9  776.71   257.5  783.04   272.6  790.71   283.9  799.26     288  803.03
   297.6   816.8   302.8  822.63   306.6  825.07   314.9  826.66   321.7   830.2
   328.9  836.01   341.2  848.98     352  856.84   355.8  862.46   367.1   884.1
   370.9  889.07   374.7  891.73   387.4  897.85     413  917.91   425.3  924.68
#Mann= 3 ,-1,0
       0      .1       0  192.15    .045       0   247.4      .1       0
#XS Ineff= 2 , 0
          158.14  796.78
Permanent Ineff=
       F       F
Bank Sta=192.15,247.4
XS Rating Curve= 0 ,0
Exp/Cntr(USF)=0,0
Exp/Cntr=0.3,0.1

Type RM Length L Ch R = 1 ,10808   ,300.8,300,298.5
XS GIS Cut Line= 6
1633741.80620326  458140.32351851633827.59015243458157.592512846
1633900.95385084458173.1741745921633998.77189668458193.949723586
  1634072.135267458209.531385332 1634157.7259751458227.710154757
#Sta/Elev= 30
       0  847.33    37.9  830.15    44.6  824.82    54.6  815.01    74.7  799.24
    84.7  792.25   104.9  780.56   111.6  778.88   128.3  777.13   138.4  777.94
   155.2  776.82   168.6  778.06  185.25771.4456   192.1  770.09     229  769.71
   235.7  770.21  238.89 771.446   249.1  777.59   255.8  780.27   262.5  781.68
   275.9  782.11   282.6  783.83   316.2  802.38     342  825.42   346.4  828.39
   376.5  835.68   379.9  837.48   387.1  846.72   396.7  853.33     425  860.88
#Mann= 3 ,-1,0
       0      .1       0  185.25    .045       0  238.89      .1       0
#XS Ineff= 2 , 0
          166.67  791.28
Permanent Ineff=
       F       F
Bank Sta=185.25,238.89
XS Rating Curve= 0 ,0
Exp/Cntr(USF)=0,0
Exp/Cntr=0.3,0.1

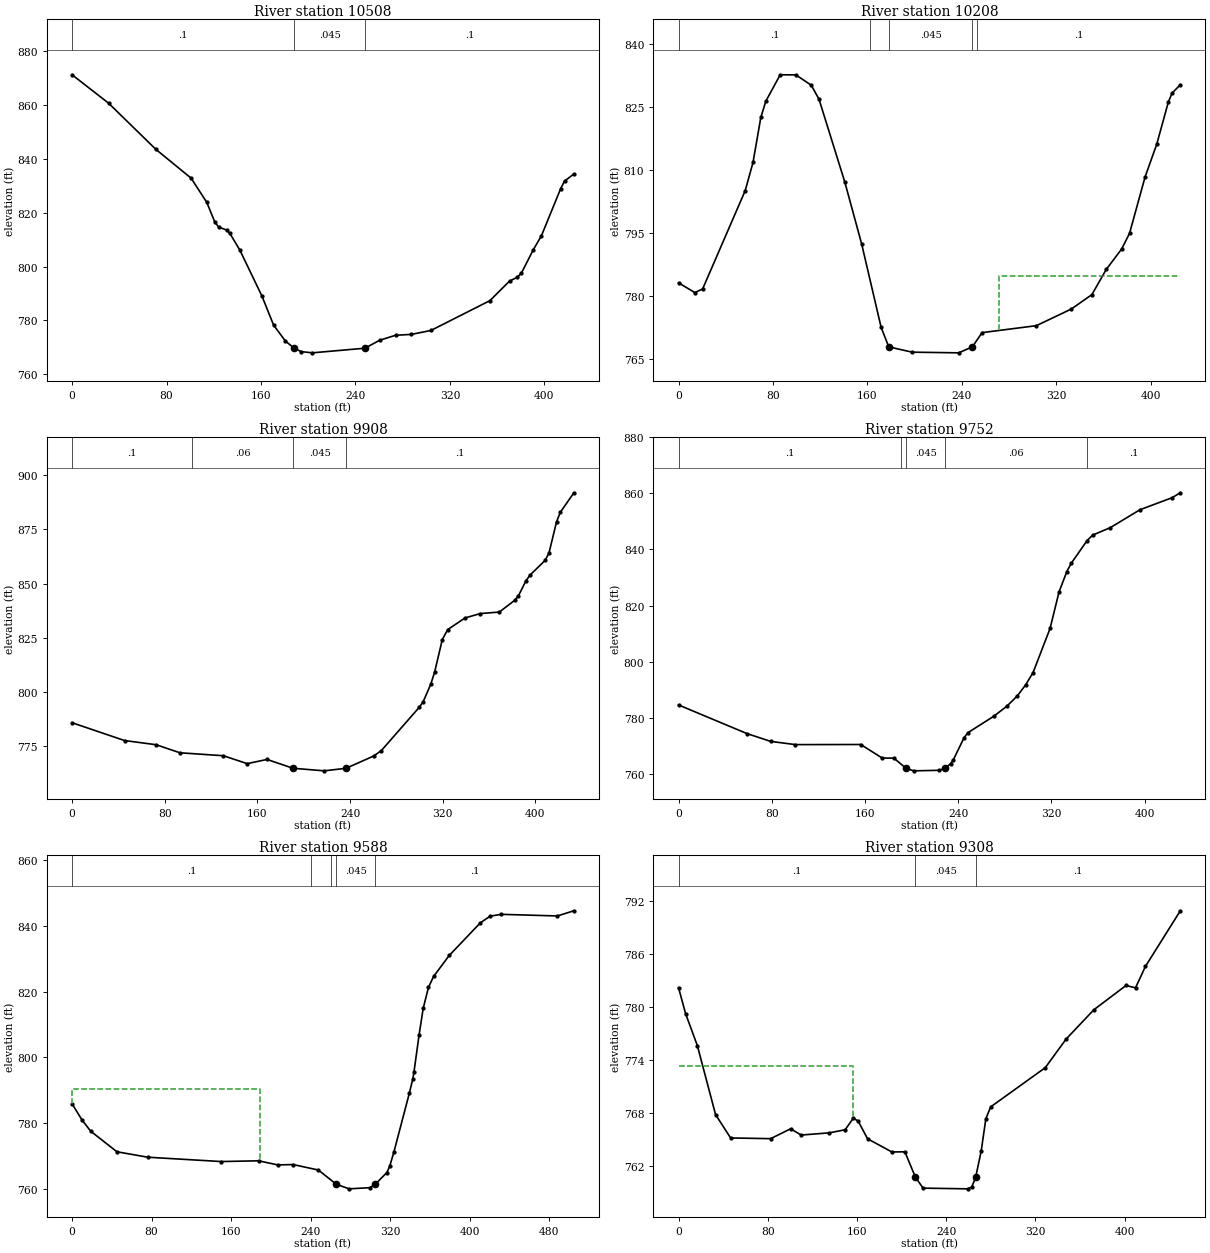
Type RM Length L Ch R = 1 ,10508   ,303.2,300,296.1
XS GIS Cut Line= 6
1633676.33783026458439.8750847581633762.55386518458454.810422346
1633836.45299558458467.6119059181633934.98560692458484.680769429
1634008.88506542   458497.4822531634095.10110034458512.416934416
#Sta/Elev= 30
       0  871.29    30.9  860.75    70.9  843.61   100.8  832.88   114.1  823.89
   120.8  816.66   124.1  814.72   130.8  813.61   133.6   812.4   142.1  806.14
   160.8  789.09   170.7  778.27   180.7  772.34  188.17769.6902   194.1  768.42
   203.4  767.97     248  769.69   260.6  772.66     274   774.5   287.3  774.82
   303.9  776.28   353.9  787.36   370.5  794.62   377.2  796.08   380.6  797.62
   390.5  806.17   397.5  811.43   413.8  828.96   417.1   831.8     425   834.4
#Mann= 3 ,-1,0
       0      .1       0  188.17    .045       0     248      .1       0
Bank Sta=188.17,248
XS Rating Curve= 0 ,0
Exp/Cntr(USF)=0,0
Exp/Cntr=0.3,0.1

Type RM Length L Ch R = 1 ,10208   ,299.6,300,297.2
XS GIS Cut Line= 6
1633640.54098584 458760.281268091633727.86167733458765.882962927
1633802.70798434458770.6844625031633902.50240417458777.086024508
1633977.34871118458781.8875240831634064.66907459458787.489546999
#Sta/Elev= 30
       0  783.11    13.8  780.78    20.4  781.64    56.5  805.11    63.1  811.83
    69.7  822.54      74  826.45    86.1  832.71    99.3  832.69   112.4  830.23
     119  826.86   140.8  807.16   155.1  792.37   171.6  772.47  178.07767.8333
   197.9  766.57   237.3  766.41  248.85767.8356   257.1  771.23   303.1  772.89
   332.7  776.86   350.1  780.29   362.3  786.32   375.4   791.2     382  794.92
   395.1  808.31     405  816.13   414.9  826.26   418.1  828.36     425  830.33
#Mann= 5 ,-1,0
       0      .1       0   162.5     .06       0  178.07    .045       0
  248.85     .06       0   252.5      .1       0
#XS Ineff= 2 , 0
                          271.32          784.68
Permanent Ineff=
       F       F
Bank Sta=178.07,248.85
XS Rating Curve= 0 ,0
Exp/Cntr(USF)=0,0
Exp/Cntr=0.3,0.1

Type RM Length L Ch R = 1 ,9908    ,141.3,156,163.1
XS GIS Cut Line= 6
1633650.07213476459019.9949875031633740.37740034459045.763636753
1633814.10395892459067.2271765021633913.87869376459073.933199838
1633988.70990892459078.9630454181634076.01288392459084.830815837
#Sta/Elev= 30
       0  785.63    45.3   777.4    72.6  775.46    93.1  771.74   130.7  770.37
   151.2  766.71   168.3  768.66  190.77764.5778   217.7  763.39  236.57764.5762
   260.4  770.25     267  772.75   299.9  792.87   303.2  795.44   309.7   803.5
     313  809.04   319.6  824.05   324.3  828.71   339.3  834.09   352.5  836.11
   368.9  836.81   382.1  842.23   385.4  844.38   391.8  851.22   395.3  853.84
   408.4  860.71   411.7  864.08   418.3  878.62   421.5  882.91   433.2  891.95
#Mann= 4 ,-1,0
       0      .1       0  103.91     .06       0  190.77    .045       0
  236.57      .1       0
Bank Sta=190.77,236.57
XS Rating Curve= 0 ,0
Exp/Cntr(USF)=0,0
Exp/Cntr=0.3,0.1

Type RM Length L Ch R = 1 ,9752    ,156.9,163.5,166.1
XS GIS Cut Line= 3
1633625.09319084459053.669852925 1633694.8719271459152.381235931
1633970.58303136459293.705301829
#Sta/Elev= 30
       0  784.55      59   774.3    79.1  771.56   100.3  770.41   156.4  770.45
   174.8  765.62   184.8  765.59  195.35  761.94   201.9  761.06   223.8  761.25
   228.7  761.94   233.6  763.62     236   765.1   244.9  772.74   248.2  774.61
   270.7  780.56   281.7  784.07   290.7  787.74   297.9  791.69   304.3   796.1
   318.9  811.84   326.6  824.84   333.3  832.13     337  835.02   350.6  843.12
   355.4  845.09   370.7  847.79     396  854.14   423.6  858.44   430.7   860.2
#Mann= 5 ,-1,0
       0      .1       0  190.88     .06       0  195.35    .045       0
   228.7     .06       0  350.88      .1       0
Bank Sta=195.35,228.7
XS Rating Curve= 0 ,0
Exp/Cntr(USF)=0,0
Exp/Cntr=0.3,0.1

Type RM Length L Ch R = 1 ,9588    ,275.7,280.5,286.9
XS GIS Cut Line= 2
1633481.19156048459155.723339993  1633873.930939459472.553793669
#Sta/Elev= 30
       0  785.82    10.1  780.86    18.7   777.5    45.1  771.22    76.2  769.56
   150.1  768.24   187.5  768.47   206.8  767.22   222.4  767.32   247.7  765.66
   265.5  761.37   278.5  759.93   299.5  760.28  305.04  761.38   316.6   764.9
   319.4  766.78   323.6  771.11   339.1  788.99   342.7  793.49   343.8  795.47
   348.9  806.68   353.1   814.9   358.4   821.3   363.6  824.64   379.3  831.02
   410.6  840.96   420.5  842.98   431.5  843.54     488  843.04   504.6  844.62
#Mann= 5 ,-1,0
       0      .1       0     240     .06       0     260      .1       0
   265.5    .045       0  305.04      .1       0
#XS Ineff= 2 , 0
           188.7  790.43
Permanent Ineff=
       F       F
Bank Sta=265.5,305.04
XS Rating Curve= 0 ,0
Exp/Cntr(USF)=0,0
Exp/Cntr=0.3,0.1

Type RM Length L Ch R = 1 ,9308    ,79.6,86,92.8
XS GIS Cut Line= 6
1633364.25996972459377.8486135311633444.63389733459452.889791012
 1633492.2565055459510.8302919271633555.75309767459588.084074423
1633603.37570584459646.024575338  1633677.632119459697.020208254
#Sta/Elev= 30
       0  782.18     6.3  779.25    16.9   775.6    33.2  767.79    46.7  765.14
    82.6  765.06   100.5  766.18     110  765.47   135.3  765.72   149.4  766.07
   156.7  767.37     161  767.07   169.5  765.05   191.3  763.55     203  763.57
  212.38760.7028   219.3  759.45   259.3  759.37   262.9  759.56  266.49760.7012
   271.4  763.64   275.6  767.32   279.9  768.66   328.9  773.11   347.5  776.34
   372.4  779.67   401.3  782.43   409.8  782.16   418.7  784.59     450   790.9
#Mann= 3 ,-1,0
       0      .1       0  212.38    .045       0  266.49      .1       0
#XS Ineff= 2 , 0
          156.15   773.3
Permanent Ineff=
       F       F
Bank Sta=212.38,266.49
XS Rating Curve= 0 ,0
Exp/Cntr(USF)=0,0
Exp/Cntr=0.3,0.1

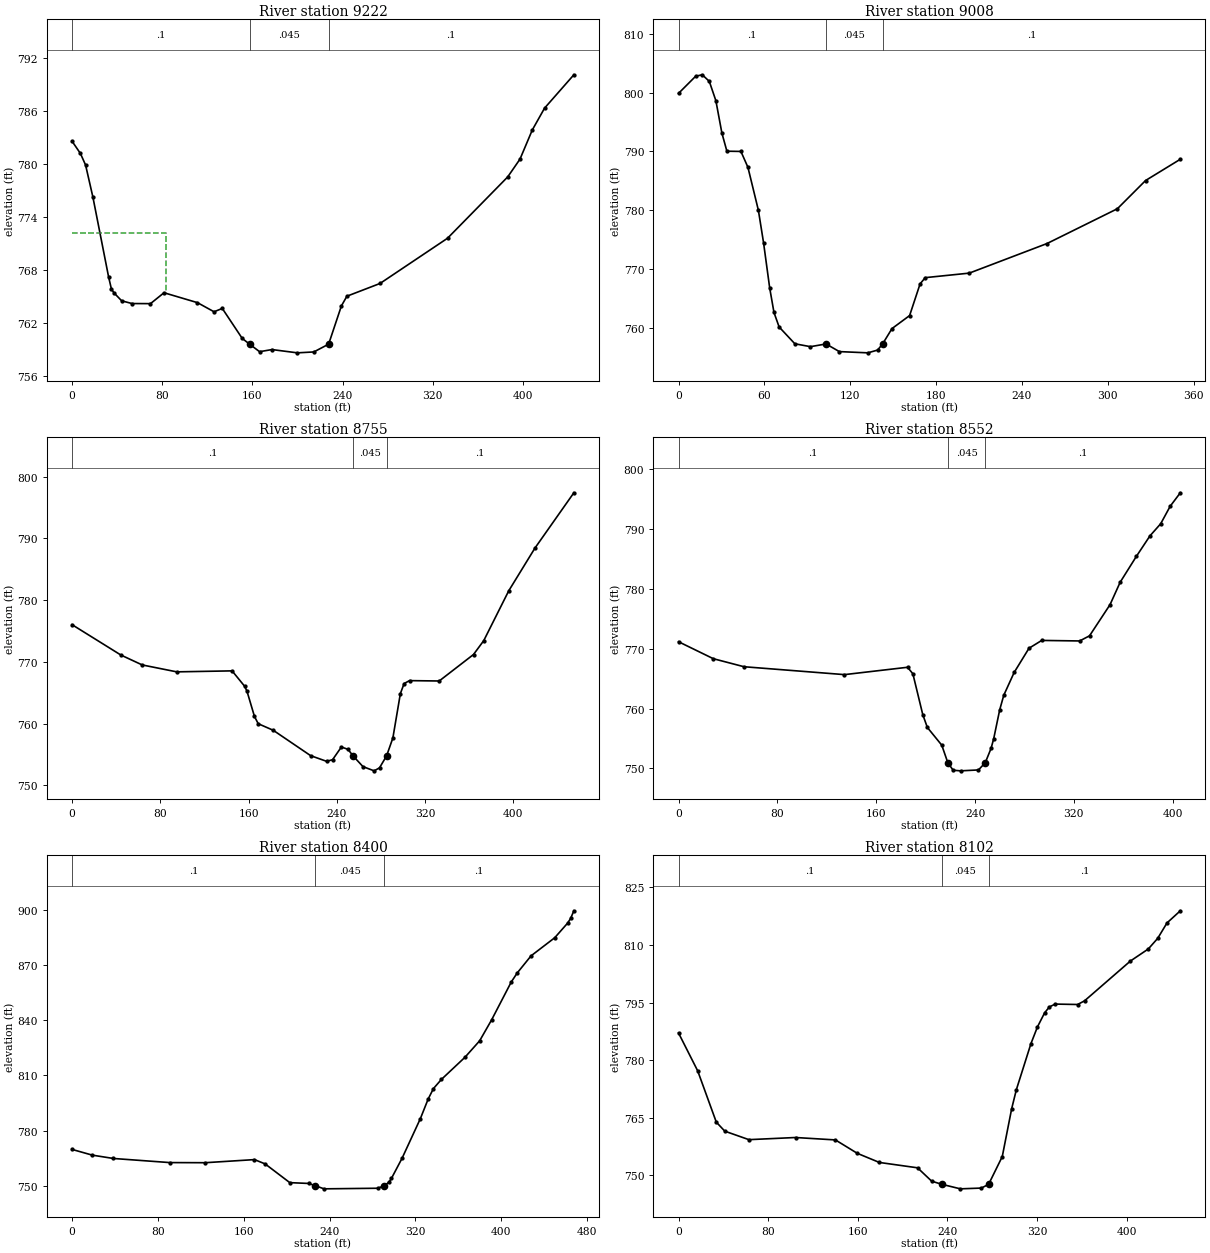
Type RM Length L Ch R = 1 ,9222    ,263,214,172.5
XS GIS Cut Line= 4
 1633340.6247148459445.1283628461633412.25876077459515.134362324
1633480.63671375459651.076245033 1633654.8376892459734.106616507
#Sta/Elev= 30
       0  782.56     7.4  781.18      12  779.87    18.5  776.24    32.4  767.24
    34.9  765.87    37.1  765.44      44  764.53    53.2  764.22    69.6  764.21
    81.6  765.44   111.3  764.32     126  763.29   133.3  763.67     151  760.28
  157.55759.6304   166.4  758.78   177.4  759.02   199.9  758.65   214.5  758.75
  227.68759.6304     239  763.95   243.9  765.05   273.3  766.49   333.2   771.6
   386.6  778.53   397.5  780.54   408.4  783.83   419.3   786.3   445.3  790.07
#Mann= 3 ,-1,0
       0      .1       0  157.55    .045       0  227.68      .1       0
#XS Ineff= 2 , 0
           83.06  772.23
Permanent Ineff=
       F       F
Bank Sta=157.55,227.68
XS Rating Curve= 0 ,0
Exp/Cntr(USF)=0,0
Exp/Cntr=0.3,0.1

Type RM Length L Ch R = 1 ,9008    ,251.4,252.6,256.6
XS GIS Cut Line= 5
1633321.94155742459841.569459841 1633389.4535615459808.902530417
 1633479.4694576459765.3465151791633552.85907459 459744.82719925
1633652.37363935 459746.42168425
#Sta/Elev= 30
       0  799.86      12  802.78    16.6  803.02    21.5   801.9    26.1  798.61
    30.3  793.11    33.8  790.02    43.6  789.98    48.5  787.28    55.8  779.98
    59.4  774.48    63.7  766.77    66.7  762.59    70.3  760.12    81.3  757.26
    92.2  756.77   103.1  757.23   112.4  755.93   132.3  755.72   139.1  756.19
  142.61  757.23   149.2  759.85   161.5  762.06   168.8  767.44   172.4  768.51
   203.2  769.28   257.5  774.31   306.7  780.23   326.4  785.03   350.7  788.65
#Mann= 3 ,-1,0
       0      .1       0   103.1    .045       0  142.61      .1       0
Bank Sta=103.1,142.61
XS Rating Curve= 0 ,0
Exp/Cntr(USF)=0,0
Exp/Cntr=0.3,0.1

Type RM Length L Ch R = 1 ,8755    ,187.2,203.4,222.8
XS GIS Cut Line= 3
1633351.22172666459924.3982061331633428.36719107460043.798925549
1633731.01095886459964.698598074
#Sta/Elev= 30
       0  776.04    44.3  771.12    63.6  769.52    94.9   768.4   145.1  768.56
   156.5  766.06   158.6  765.27   165.4  761.17   168.8     760   182.4  758.94
   216.3  754.83   230.8  753.91   236.2  754.17   244.2  756.23   250.2  755.85
     255  754.75   263.8  753.05   273.9  752.37   278.8  752.86  285.22  754.81
   290.9   757.7   297.7  764.89   301.1  766.51     306  766.98   332.9  766.92
     364  771.21   373.3  773.46     396  781.54   419.7  788.44     455   797.4
#Mann= 3 ,-1,0
       0      .1       0     255    .045       0  285.22      .1       0
Bank Sta=255,285.22
XS Rating Curve= 0 ,0
Exp/Cntr(USF)=0,0
Exp/Cntr=0.3,0.1

Type RM Length L Ch R = 1 ,8552    ,124.9,152.4,178.3
XS GIS Cut Line= 3
1633333.79249575 459938.515286351633398.58460525460099.806282341
 1633537.8187129460285.911277715
#Sta/Elev= 30
       0  771.17    28.2  768.33      53  766.99   134.3  765.67   185.4   766.9
   189.7  765.81   197.7  758.99   201.4  756.84   213.1  753.87  217.98  750.94
   222.3  749.68   228.3  749.58   242.8  749.73   248.3  750.94     253  753.34
   255.1  754.93     260   759.8   263.3  762.23   271.7  766.04   283.7  770.08
     294  771.39   324.7   771.3   332.7  772.16   349.3  777.37   357.5  781.12
   370.6  785.44   381.6  788.87   390.3   790.9     398  793.83   406.2  796.08
#Mann= 3 ,-1,0
       0      .1       0  217.98    .045       0   248.3      .1       0
Bank Sta=217.98,248.3
XS Rating Curve= 0 ,0
Exp/Cntr(USF)=0,0
Exp/Cntr=0.3,0.1

Type RM Length L Ch R = 1 ,8400    ,289.4,297.5,306.5
XS GIS Cut Line= 5
1633308.75925274459932.7007435681633318.62791575460137.327726588
1633279.37077643460229.5676995961633245.23731451460296.350046337
1633205.41521567460374.263276339
#Sta/Elev= 30
       0  769.82    18.9   766.7    38.6  764.89    91.1  762.66     124  762.59
     170  764.28   179.9  761.94   202.9  751.76   220.5  751.32 226.733750.0844
   234.8  748.39   284.7  748.71 291.133750.0903   295.4  752.07   297.6  754.05
   307.5     765   324.6  786.59   331.9   797.3   336.8  802.92   344.1  807.82
   366.1  819.88   379.8  828.84   390.9  840.16   409.3  860.85   414.8  865.71
   427.7  875.02   449.8  884.88   461.7  892.76   464.6  895.36   467.6  899.52
#Mann= 3 ,-1,0
       0      .1       0 226.733    .045       0 291.133      .1       0
Bank Sta=226.733,291.133
XS Rating Curve= 0 ,0
Exp/Cntr(USF)=0,0
Exp/Cntr=0.3,0.1

Type RM Length L Ch R = 1 ,8102    ,281,282.6,285.4
XS GIS Cut Line= 6
1633220.39429504459816.7552731421633152.67910068459903.629047006
1633102.17001534459959.2683714181633039.70032401460037.355157509
1632992.84805551460095.9203290941632938.18707559460164.245979846
#Sta/Elev= 30
       0  787.05    17.1  777.18    33.7  763.82    41.3  761.46    62.8  759.25
   104.4  759.81     140  759.18   159.5  755.69   179.2  753.31   213.3  751.91
   225.9  748.43234.9478747.6136   251.5  746.43   270.2  746.63276.7078747.6014
   288.9  754.84   297.3  767.33   301.5   772.3   314.5  784.29   320.3  788.64
   326.7  792.31   330.9  793.84   336.1  794.59   356.1  794.48   362.3  795.43
   403.2   805.8   419.2  808.95   427.6  811.72   435.9  815.74   447.8  818.91
#Mann= 3 ,-1,0
       0      .1       0234.9478    .045       0276.7078      .1       0
Bank Sta=234.9478,276.7078
XS Rating Curve= 0 ,0
Exp/Cntr(USF)=0,0
Exp/Cntr=0.3,0.1

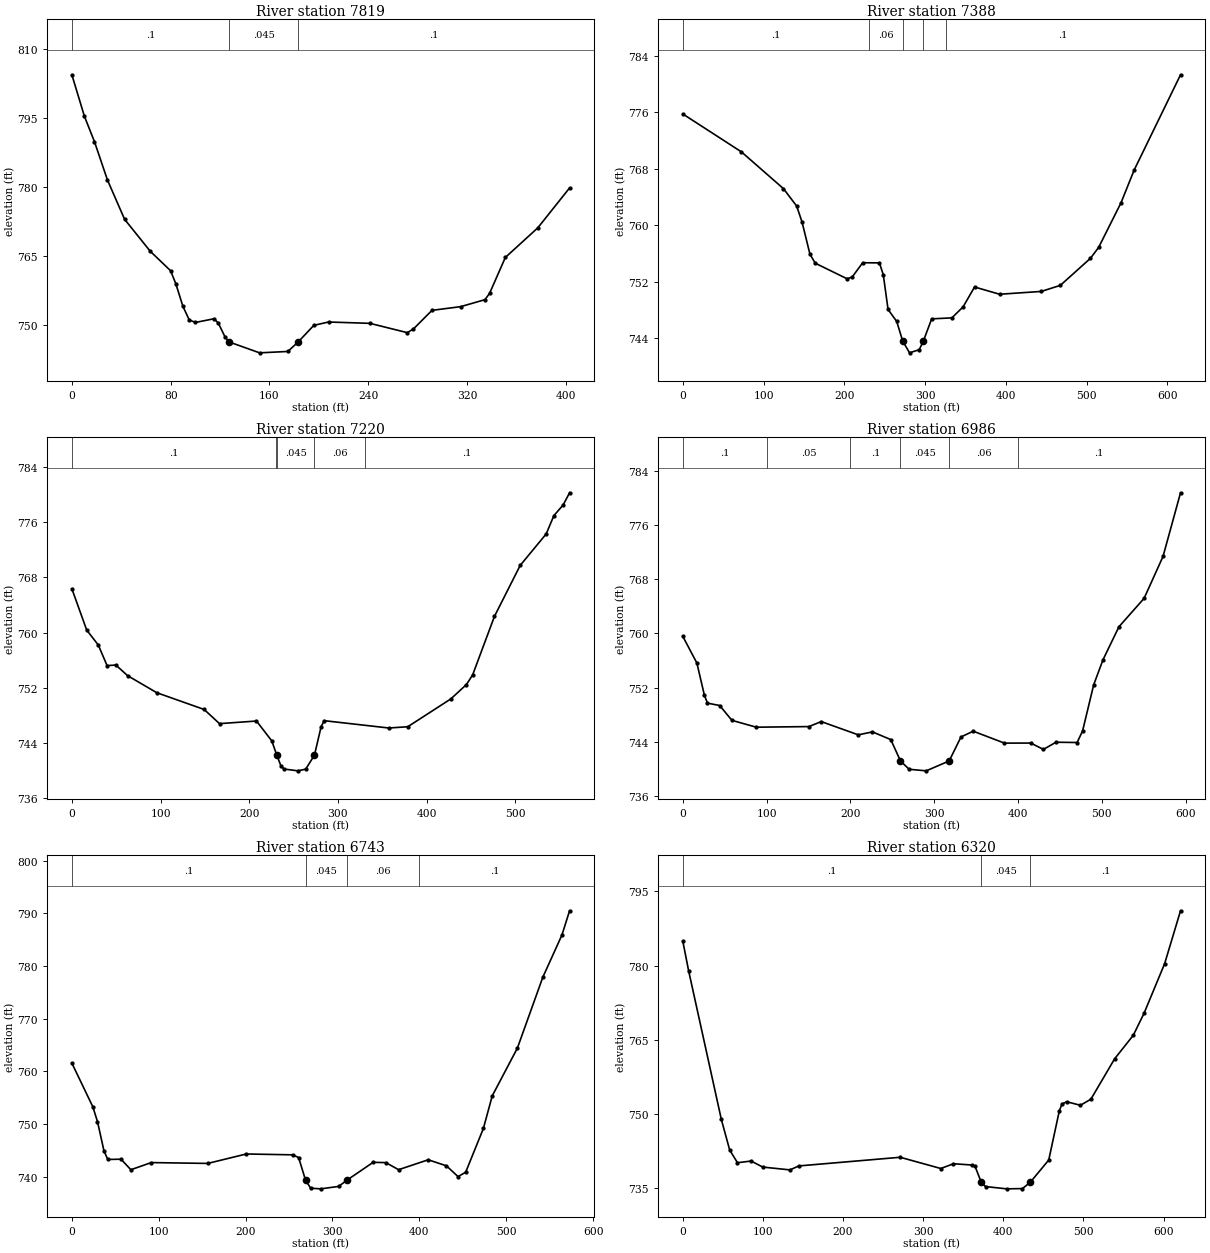
Type RM Length L Ch R = 1 ,7819    ,455.5,431.5,411.8
XS GIS Cut Line= 4
 1633036.0019067459663.3125092531632981.04122101459716.471066253
1632810.26598894459862.5946629561632802.63846925459964.116829019
#Sta/Elev= 30
       0  804.36    10.2  795.32    18.3  789.85    28.8  781.54    42.7     773
    63.6  766.03    79.9  761.86    84.2     759    89.9  754.13      95  751.19
     100  750.62   115.2  751.43   118.7  750.42   124.1  747.43  127.18 746.404
     152  744.03   174.9  744.33   183.3746.4037   195.9  749.99   207.8  750.72
   241.3  750.43   271.6  748.41   276.6  749.22   291.6  753.25   314.8  754.05
   334.5  755.57   338.2  756.92     351  764.73   377.3  771.16     403  779.81
#Mann= 3 ,-1,0
       0      .1       0  127.18    .045       0   183.3      .1       0
Bank Sta=127.18,183.3
XS Rating Curve= 0 ,0
Exp/Cntr(USF)=0,0
Exp/Cntr=0.3,0.1

Type RM Length L Ch R = 1 ,7388    ,164.4,167.9,169.5
XS GIS Cut Line= 5
1632614.67197458 459380.815788181632614.55007889459616.110467482
1632667.30961119459738.6487360391632696.24225793459781.196745955
1632744.67682119 459971.18059648
#Sta/Elev= 30
       0  775.79    72.5  770.42   124.6   765.2     141  762.72   147.6  760.47
   157.4   755.9     164  754.62   203.3  752.42   209.6  752.65   222.7  754.69
   243.4  754.67   248.2  752.99   254.1  748.06   264.8  746.37  272.21743.5875
   280.7  741.91   292.7  742.36  297.84743.5865   308.1  746.73   333.1  746.87
     347  748.43   361.2  751.25   392.2  750.22   443.7  750.62   467.4  751.48
   504.6  755.31   514.8  756.86   542.5  763.19   558.8  767.84   616.2  781.35
#Mann= 5 ,-1,0
       0      .1       0     230     .06       0  272.21    .045       0
  297.84     .06       0  325.29      .1       0
Bank Sta=272.21,297.84
XS Rating Curve= 0 ,0
Exp/Cntr(USF)=0,0
Exp/Cntr=0.3,0.1

Type RM Length L Ch R = 1 ,7220    ,237.6,234.4,232.3
XS GIS Cut Line= 6
1632465.31478281459498.6789413731632452.45346701459633.487855002
1632476.87861501459704.3991305081632509.44547901459798.947497845
  1632533.870627459869.8587733361632597.59638522460033.770197669
#Sta/Elev= 30
       0  766.34    16.7  760.37    29.8   758.2    39.7  755.22    49.6   755.3
    62.8  753.77    95.7   751.3   149.2  748.87   166.5  746.82   208.2   747.2
   225.5  744.32  231.06742.2715   235.9  740.67   239.4  740.25   254.9  739.99
   263.7  740.23  273.61742.2707     281  746.33   284.5  747.25   357.4  746.19
   378.8  746.37   427.4   750.4     445  752.48     452  753.88   476.6  762.35
   505.6  769.72   534.9  774.27   543.6  776.92   554.1  778.48   561.3  780.23
#Mann= 5 ,-1,0
       0      .1       0  230.42     .06       0  231.06    .045       0
  273.61     .06       0  330.42      .1       0
Bank Sta=231.06,273.61
XS Rating Curve= 0 ,0
Exp/Cntr(USF)=0,0
Exp/Cntr=0.3,0.1

Type RM Length L Ch R = 1 ,6986    ,248.8,242.4,233.1
XS GIS Cut Line= 2
1632150.90935054459580.6739920031632410.15798333460115.128766308
#Sta/Elev= 30
       0  759.56    16.8  755.62    25.7   750.9    29.4  749.71      44  749.36
    58.6  747.17    87.7  746.16   150.5  746.25   165.2  746.99   209.4  745.03
   226.3  745.47   248.2  744.33  259.76741.1788   270.1  739.95   290.5  739.72
  317.89741.1796     332  744.72   346.6  745.57   383.8  743.81   415.2  743.82
   430.4  742.88   445.3  743.94   470.6   743.9   477.1  745.61   490.4  752.43
   501.5  756.12   520.5  760.98   550.5  765.17   573.1  771.35     594  780.75
#Mann= 6 ,-1,0
       0      .1       0     100     .05       0     200      .1       0
  259.76    .045       0  317.89     .06       0     400      .1       0
Bank Sta=259.76,317.89
XS Rating Curve= 0 ,0
Exp/Cntr(USF)=0,0
Exp/Cntr=0.3,0.1

Type RM Length L Ch R = 1 ,6743    ,387.8,423.2,439.4
XS GIS Cut Line= 2
1631889.09524195459770.1023126761632274.12131747460194.332704794
#Sta/Elev= 30
       0  761.58    24.1  753.31    29.5  750.49    36.9  744.98    41.3  743.31
    56.6  743.36    67.9  741.36    91.4  742.72   156.4  742.56   200.8  744.35
     254  744.19     261  743.68  268.98 739.378   274.9  737.86   286.5  737.74
   307.1   738.2  316.62739.3797   346.8  742.77   361.4  742.71   376.1  741.37
   410.2  743.25   431.2   742.1   444.5  740.06   453.3  740.89   473.7   749.2
   483.9  755.38   512.8  764.42   542.1  777.87   564.1  785.87   572.9  790.47
#Mann= 4 ,-1,0
       0      .1       0  268.98    .045       0  316.62     .06       0
     400      .1       0
Bank Sta=268.98,316.62
XS Rating Curve= 0 ,0
Exp/Cntr(USF)=0,0
Exp/Cntr=0.3,0.1

Type RM Length L Ch R = 1 ,6320    ,315.1,306,298.9
XS GIS Cut Line= 6
1631694.94489032459866.551116389  1631828.572825460116.268057421
1631831.66927551460191.6081298441631825.43109901460291.413376421
1631820.75230259460366.2672293341631818.59088959460453.802815422
#Sta/Elev= 30
       0  784.91     7.2  778.97    48.1  748.88    58.5  742.71    68.2  740.14
    85.3  740.48    99.7  739.26   133.7  738.69   144.8  739.49   271.3  741.24
     322  738.97   337.8  739.93   361.4  739.67   364.7  739.42  372.45 736.212
   377.8  735.32   404.1  734.86   423.9  734.91  433.81736.2117   456.7  740.68
   469.9  750.61   473.2     752   479.2  752.46   496.2  751.75   509.3  752.97
   538.9  761.13   562.2  765.89   575.6  770.32   601.3  780.34   621.2  791.06
#Mann= 3 ,-1,0
       0      .1       0  372.45    .045       0  433.81      .1       0
Bank Sta=372.45,433.81
XS Rating Curve= 0 ,0
Exp/Cntr(USF)=0,0
Exp/Cntr=0.3,0.1