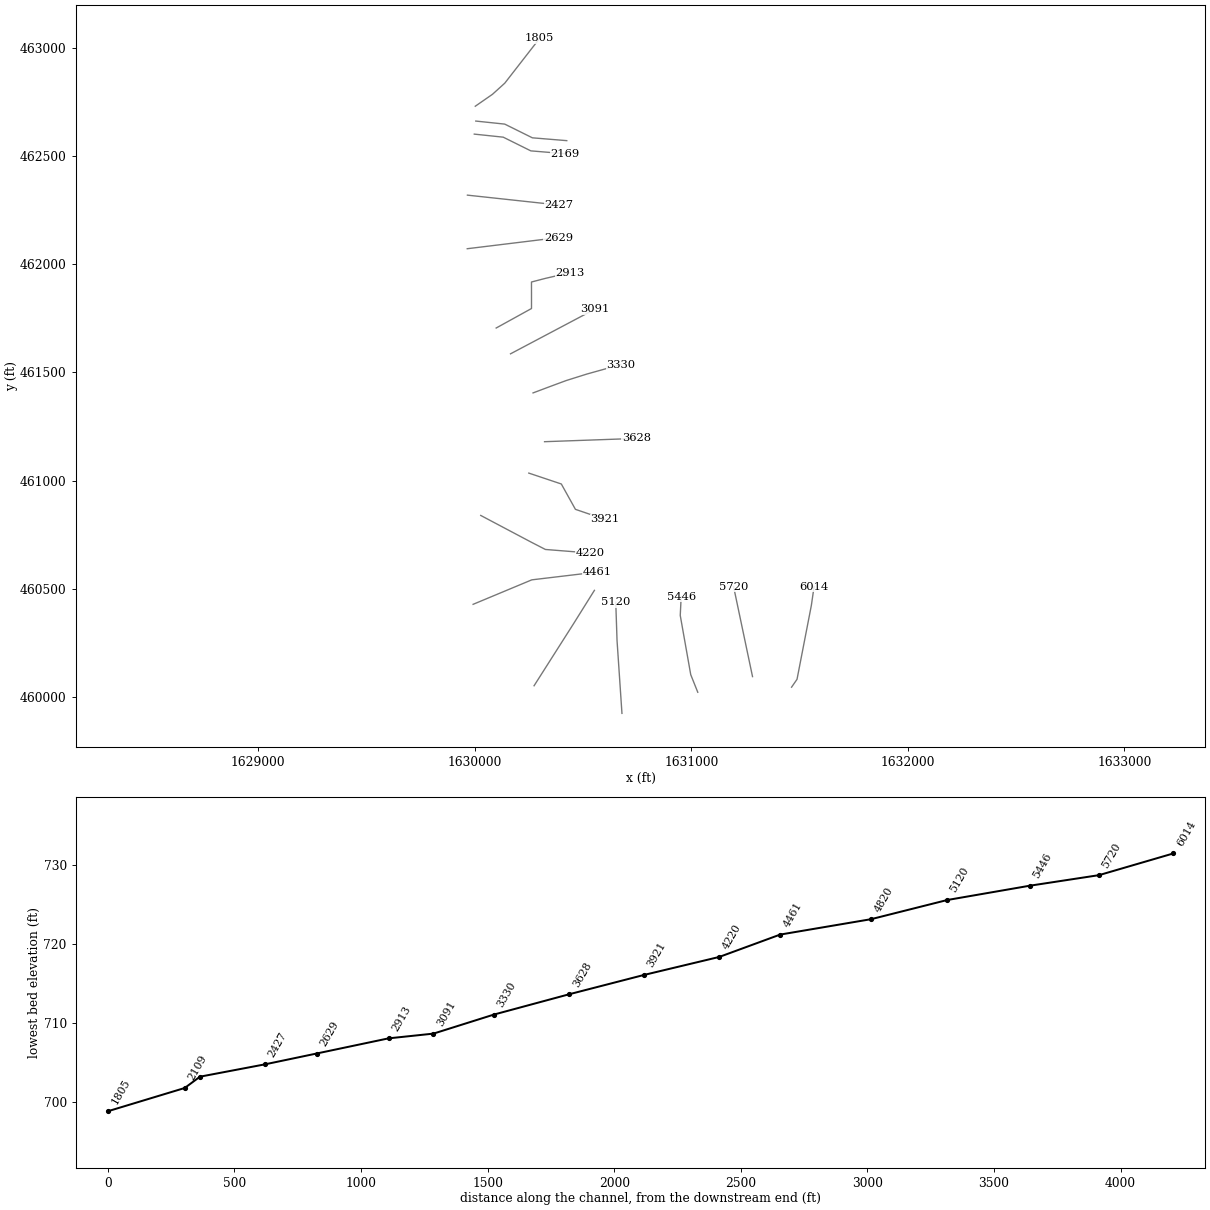
HEC-RAS study LynCmpRn.prj: LynCmpRn

--- LynCmpRn.g01 (geometry) --- (continued)

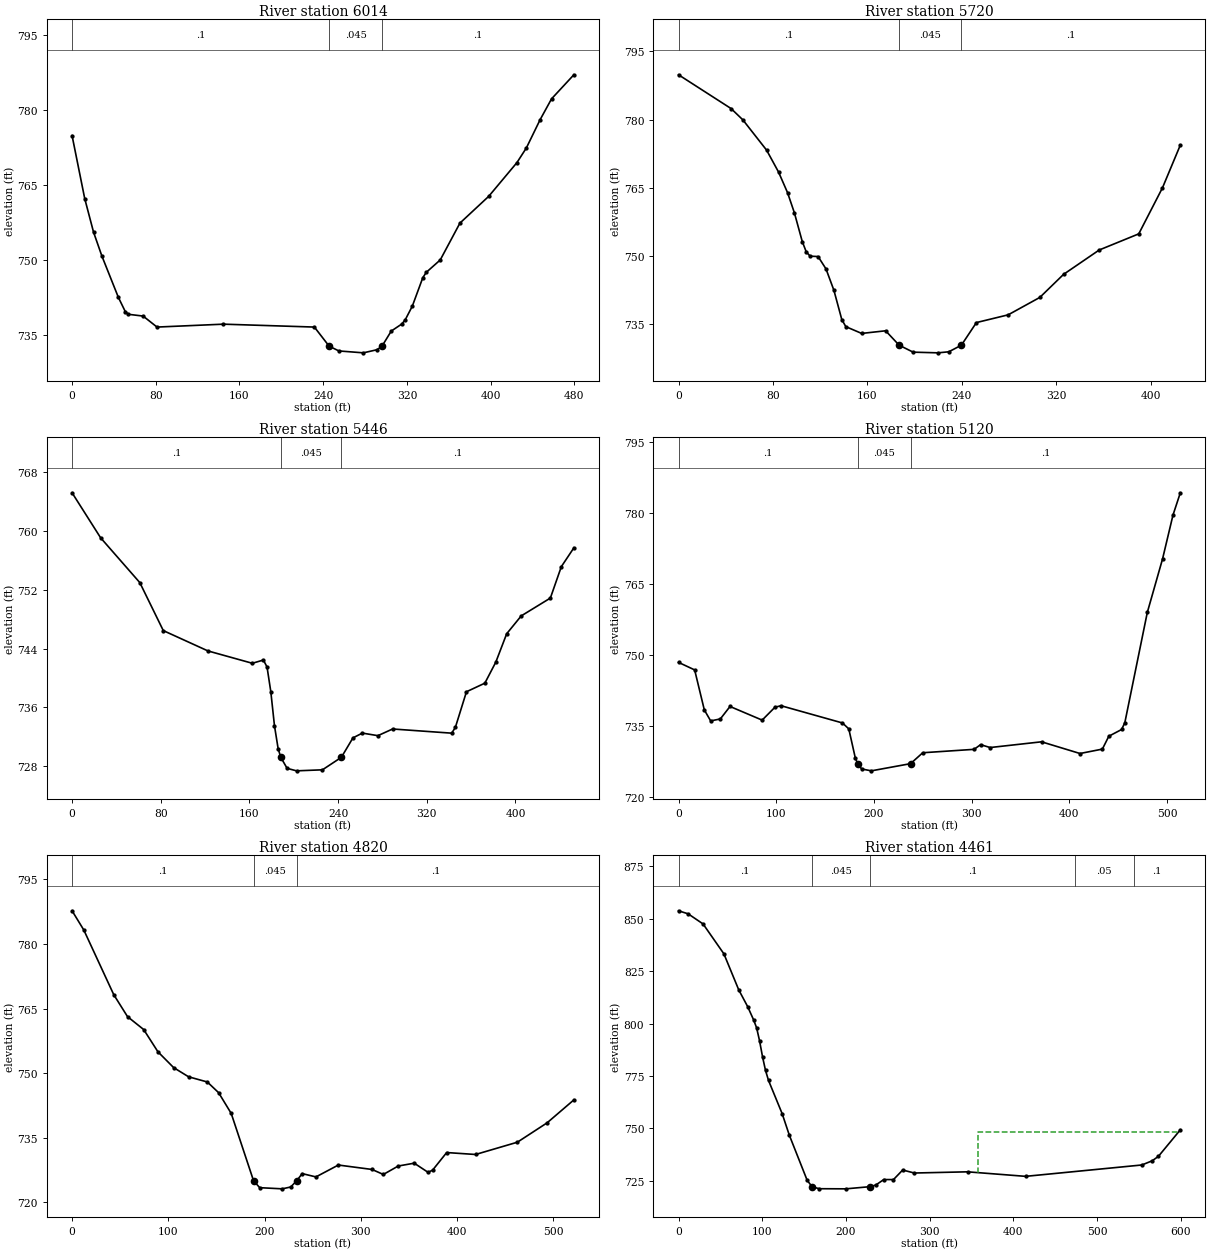
Type RM Length L Ch R = 1 ,6014    ,284.3,294,304.9
XS GIS Cut Line= 4
1631462.72417591460046.2539188751631487.94515122460082.693646137
1631554.15539484460424.1358800081631566.70589468460510.731179252
#Sta/Elev= 30
       0  774.92    12.1  762.31    20.5  755.61    28.5  750.81    44.3  742.51
    50.9  739.67    53.7  739.15    67.9  738.79    81.2  736.59   144.7  737.17
   231.6  736.59  245.67732.7742     255  731.81   278.4  731.43   291.6  732.06
  296.25732.7739   305.1  735.79   315.2  737.21   318.5  738.07   325.2  740.78
   335.2  746.46   338.5  747.54   351.9  750.03   370.7   757.4   398.2  762.76
   425.2  769.52   434.2  772.45   447.4  778.13   458.3  782.29   479.6   787.1
#Mann= 3 ,-1,0
       0      .1       0  245.67    .045       0  296.25      .1       0
Bank Sta=245.67,296.25
XS Rating Curve= 0 ,0
Exp/Cntr(USF)=0,0
Exp/Cntr=0.3,0.1

Type RM Length L Ch R = 1 ,5720    ,274.9,274,273
XS GIS Cut Line= 6
1631282.44169943460095.0978241711631264.41548875460180.720684424
1631248.96473226460254.1122699231631228.36372359460351.967061087
1631212.91263901460425.3583185081631194.88642834460510.981178761
#Sta/Elev= 30
       0  789.84    44.5  782.41    54.5  779.92    74.6  773.26    84.7  768.45
    92.3  763.93    98.1   759.5   104.8  753.16   108.2  750.87   111.5  749.94
   118.2  749.86   124.9  747.14   131.6  742.43   138.3  735.98   141.7  734.44
   155.1  732.95   175.4  733.53  186.83730.3649   198.7  728.83   219.7  728.68
   228.9  728.91  239.57730.3631   252.3  735.34   279.2  737.04     306  740.87
   326.1  745.94   356.3   751.3   389.8  754.85   409.9  764.99     425  774.38
#Mann= 3 ,-1,0
       0      .1       0  186.83    .045       0  239.57      .1       0
Bank Sta=186.83,239.57
XS Rating Curve= 0 ,0
Exp/Cntr(USF)=0,0
Exp/Cntr=0.3,0.1

Type RM Length L Ch R = 1 ,5446    ,329,326,323.2
XS GIS Cut Line= 4
1631029.61051217460022.7892417611630997.11352992460104.030877173
1630948.68541277 460377.506501151630952.95023918 460464.87504999
#Sta/Elev= 30
       0  765.21    25.8  759.07    61.1  752.98    82.3  746.44   122.6  743.67
   162.6  741.99   172.6  742.43   175.9  741.48   179.3  738.12   182.6  733.48
   185.9  730.37  188.27729.1853     194  727.68   202.5  727.34   225.9  727.48
  242.97729.1837   253.4  731.83   261.9  732.48   275.9  732.13   289.2  733.04
   342.5  732.47   345.8  733.26   355.8  738.11   372.4  739.28   382.3  742.15
   392.1  746.01   405.2  748.44   431.5  750.87   441.4  755.15   452.7  757.71
#Mann= 3 ,-1,0
       0      .1       0  188.27    .045       0  242.97      .1       0
Bank Sta=188.27,242.97
XS Rating Curve= 0 ,0
Exp/Cntr(USF)=0,0
Exp/Cntr=0.3,0.1

Type RM Length L Ch R = 1 ,5120    ,317,300,284.6
XS GIS Cut Line= 6
1630679.48555626459925.2914052611630673.62172285460012.598317251
1630668.56530251460087.427563921   1630661.82319460187.200002179
1630656.76676968460262.0292488341630650.90260817460438.169187703
#Sta/Elev= 30
       0  748.43    16.5  746.84    26.4  738.39    32.9  736.07    42.8  736.49
    52.7  739.12    85.6  736.24    98.7  738.96   104.9  739.28   167.8  735.64
   174.3  734.39   180.9  728.31   183.3727.0518   187.5  725.92   197.4  725.53
  237.56727.0496     250  729.35   302.6  730.07   309.2  731.06     319  730.45
   371.6  731.66     411  729.19   433.9  730.12   440.5  732.84   453.6  734.26
   456.9  735.71   479.9  758.98   495.5  770.27   506.2  779.54   513.7  784.24
#Mann= 3 ,-1,0
       0      .1       0   183.3    .045       0  237.56      .1       0
Bank Sta=183.3,237.56
XS Rating Curve= 0 ,0
Exp/Cntr(USF)=0,0
Exp/Cntr=0.3,0.1

Type RM Length L Ch R = 1 ,4820    ,378.2,359.4,344.7
XS GIS Cut Line= 6
1630273.67436001 460052.893184171630320.65130018460126.713574588
1630360.91696768460189.9880543351630414.60452434460274.354027346
1630454.87019184460337.6288351711630552.27407493460493.393540983
#Sta/Elev= 30
       0   787.7    12.2  783.23    43.3  768.21    57.6  763.11    74.4  760.11
    89.2  754.94   105.5  751.27     121  749.14   140.5  747.93   152.2  745.45
   165.3  740.63  188.47725.0097   194.9  723.38   218.3  723.11   227.1  723.54
  233.42725.0117     239  726.65   253.3  725.88   276.6  728.64   311.6  727.61
   323.3  726.45   338.8  728.41   355.4  729.07   369.8  726.94   374.5  727.46
   389.1  731.54   419.1  731.09   462.5  733.94   493.4  738.44   521.2  743.77
#Mann= 3 ,-1,0
       0      .1       0  188.47    .045       0  233.42      .1       0
Bank Sta=188.47,233.42
XS Rating Curve= 0 ,0
Exp/Cntr(USF)=0,0
Exp/Cntr=0.3,0.1

Type RM Length L Ch R = 1 ,4461    ,270.3,240.6,213.2
XS GIS Cut Line= 3
1629992.13930454460428.8755357091630263.13187359 460541.92639869
1630566.85114504460578.161861161
#Sta/Elev= 30
       0  853.84    11.5  852.38    29.3  847.56    54.2  833.29    71.9  816.13
    82.6  808.09    89.7  801.77    93.3  797.96    96.8   791.8   100.4  784.08
   103.9  777.68   107.5  772.89   123.8  757.03   132.4  746.72   153.7  725.21
  159.53722.1895   167.9  721.22   199.9  721.16  228.68722.1905   235.5  722.93
   245.2  725.59   256.8  725.58   267.8  730.14   281.7  728.71   345.3  729.28
   414.7  727.12   553.5  732.54   565.9  734.54   573.3  736.66   599.5  749.32
#Mann= 5 ,-1,0
       0      .1       0  159.53    .045       0  228.68      .1       0
  473.63     .05       0  543.63      .1       0
#XS Ineff= 2 , 0
                          357.48           748.3
Permanent Ineff=
       F       F
Bank Sta=159.53,228.68
XS Rating Curve= 0 ,0
Exp/Cntr(USF)=0,0
Exp/Cntr=0.3,0.1

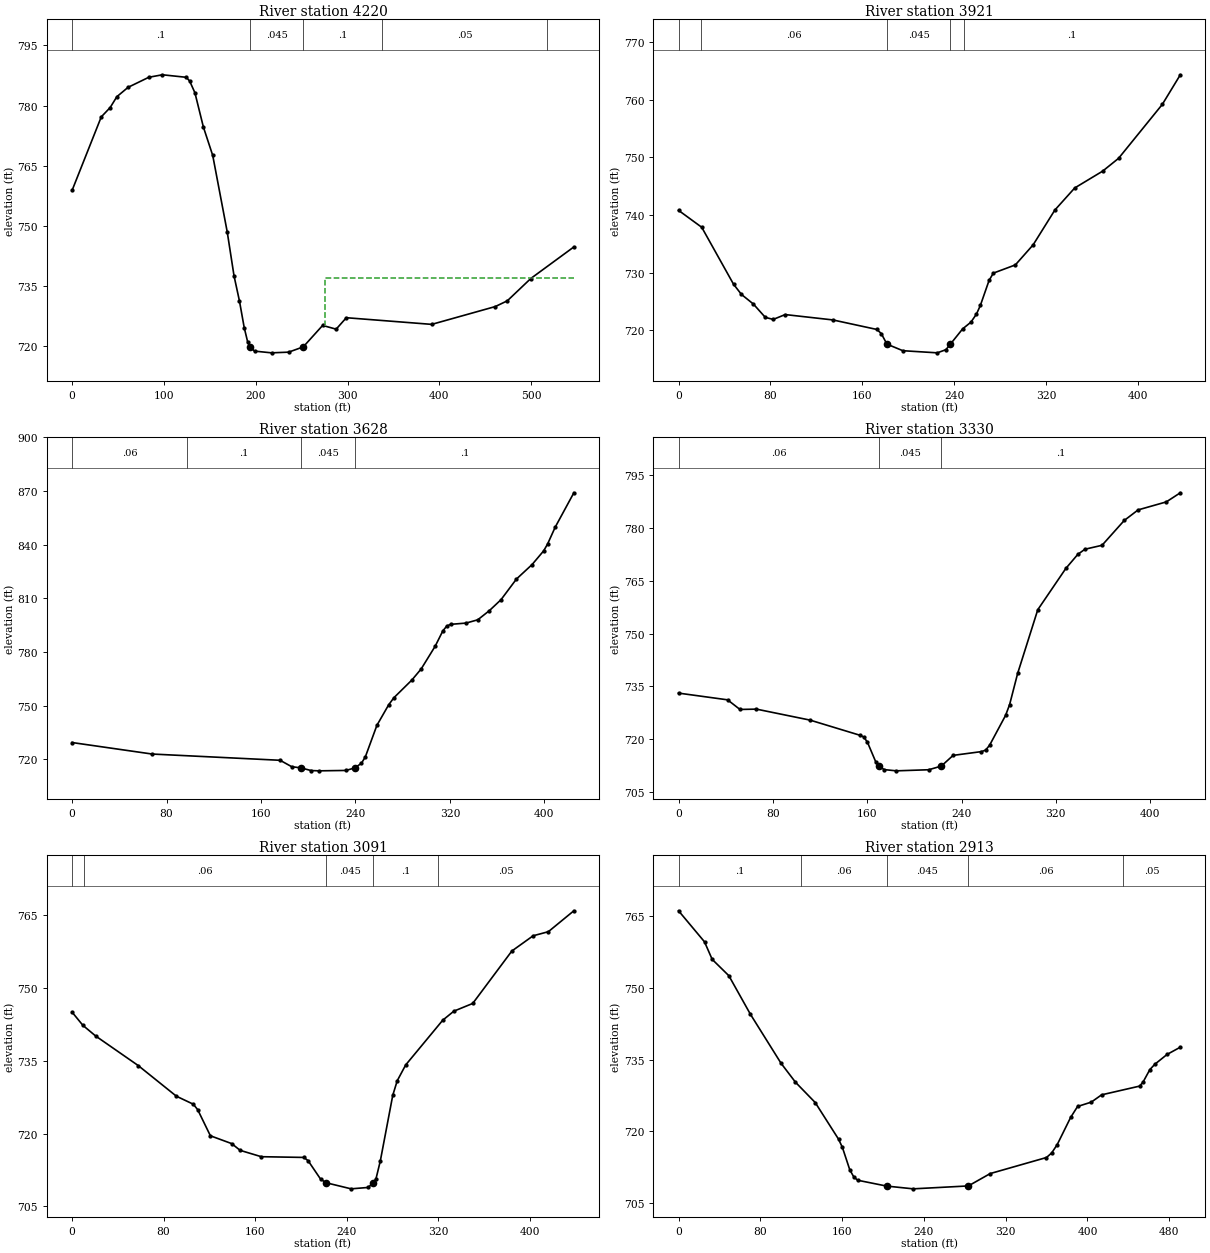
Type RM Length L Ch R = 1 ,4220    ,311.6,298.8,278.5
XS GIS Cut Line= 6
1630027.30083701460839.3584747611630104.63237526460798.418267921
1630170.91669151460763.3268026711630259.29512367460716.538182333
1630325.98495093460682.2127916661630534.33796565460665.635831981
#Sta/Elev= 30
       0  758.83    31.8  777.18    41.5  779.51    48.8  782.22      61  784.55
    83.6  787.06    98.4  787.68   124.4  787.05   128.1   786.1   133.8  783.19
     143  774.66   153.2  767.55     169  748.47   176.4  737.52   182.3  731.26
   187.5   724.6   191.3  720.99  193.83719.8112   198.7  718.76   217.2  718.33
   235.8   718.5  251.75719.8109   272.9  725.17   287.6  724.23   298.7  727.09
   391.7  725.43   460.9  729.87     474   731.3   499.6  736.87   546.5  744.74
#Mann= 5 ,-1,0
       0      .1       0  193.83    .045       0  251.75      .1       0
   337.5     .05       0   517.5      .1       0
#XS Ineff= 2 , 0
                          275.07          737.11
Permanent Ineff=
       F       F
Bank Sta=193.83,251.75
XS Rating Curve= 0 ,0
Exp/Cntr(USF)=0,0
Exp/Cntr=0.3,0.1

Type RM Length L Ch R = 1 ,3921    ,261.8,292.8,318.6
XS GIS Cut Line= 4
1630249.31231122461034.8776264551630399.45569736460984.595893852
1630464.62500795460867.5079606941630601.64384048460820.700959657
#Sta/Elev= 30
       0   740.8    20.2  737.86    47.9  727.97    54.8  726.19    65.2  724.52
    75.6   722.2    82.5  721.85    92.9  722.69   134.4  721.76   172.8   720.1
   176.6  719.39  181.53717.5532   195.4  716.41   225.4  716.04   232.9  716.59
  236.82717.5534   247.5  720.21   254.7  721.37   259.5  722.77   262.9  724.27
   270.5  728.62   274.2  729.89   293.4  731.32   308.9  734.81   327.8  740.85
   345.1  744.69   369.4  747.61   383.3  749.84   421.4  759.21   437.1  764.36
#Mann= 5 ,-1,0
       0      .1       0      20     .06       0  181.53    .045       0
  236.82     .06       0  248.34      .1       0
Bank Sta=181.53,236.82
XS Rating Curve= 0 ,0
Exp/Cntr(USF)=0,0
Exp/Cntr=0.3,0.1

Type RM Length L Ch R = 1 ,3628    ,292.6,298.4,304.9
XS GIS Cut Line= 6
1630322.10995868461179.8768225911630409.55400951461182.999191672
1630484.50628743461185.6760235881630584.44243926461189.244914085
1630659.39471717461191.9217460011630746.83909608461195.044771254
#Sta/Elev= 30
       0  729.44    67.8  723.01   176.2  719.52     186  715.94  193.86715.2693
   202.4  713.79     209  713.62     232  713.84   239.5715.2694   245.1  717.87
   248.4  721.45   258.2  739.08   268.1  750.47   272.5  754.44   287.8  764.38
   295.7   770.6   307.5  783.24     314  791.82   317.3  794.52   320.6  795.51
   333.7  796.22   343.6  798.05   353.4  803.15   363.3   809.3   376.4  820.86
   389.6  828.92   399.4  836.58   402.7  840.35   409.2  849.84     425  869.06
#Mann= 4 ,-1,0
       0     .06       0    97.5      .1       0  193.86    .045       0
   239.5      .1       0
Bank Sta=193.86,239.5
XS Rating Curve= 0 ,0
Exp/Cntr(USF)=0,0
Exp/Cntr=0.3,0.1

Type RM Length L Ch R = 1 ,3330    ,235.5,238.8,242.9
XS GIS Cut Line= 6
1630268.96111484461405.1667263361630351.18503176461436.043961167
1630421.76199034461462.1551294181630517.20110393461492.186565429
1630589.43422717461512.3699240091630673.70636834461535.916792929
#Sta/Elev= 30
       0  733.11    41.6   731.2    52.1  728.47    66.1  728.56   111.6  725.44
   153.6  721.17   157.1  720.65   160.2  719.18   167.5  713.41  170.15712.3889
   174.4  711.39   184.7  711.04   212.2  711.35  222.86 712.388   232.9  715.43
   256.9   716.5   260.4  716.92   263.8  718.29   277.4  726.79   280.8  729.84
   287.6  738.68   304.7  756.79   328.5  768.51   338.7  772.52   344.7  773.96
   359.2  775.08     378  782.12   389.8  785.13   413.7   787.4   425.6  789.99
#Mann= 3 ,-1,0
       0     .06       0  170.15    .045       0  222.86      .1       0
Bank Sta=170.15,222.86
XS Rating Curve= 0 ,0
Exp/Cntr(USF)=0,0
Exp/Cntr=0.3,0.1

Type RM Length L Ch R = 1 ,3091    ,158.5,177.5,229
XS GIS Cut Line= 2
1630164.93415506461585.690116368  1630552.582879461790.846848675
#Sta/Elev= 30
       0  745.03     9.5   742.3    20.7   740.1    57.8  734.03    91.2  727.71
     106  726.06   109.8  724.94   120.9  719.56   139.5  717.95   146.9  716.56
   165.4  715.25   202.6   715.1   206.3  714.43   217.2  710.64   222.1  709.88
   243.9  708.63   258.5  708.91   263.3   709.8   265.7  710.75   269.4  714.34
   280.3  727.89   284.2  730.89   291.6  734.15     324  743.37   333.7  745.23
   350.2  746.82   384.4  757.62     403  760.76   416.3   761.6   438.6  765.91
#Mann= 5 ,-1,0
       0     .05       0      10     .06       0   222.1    .045       0
   263.3      .1       0     320     .05       0
Bank Sta=222.1,263.3
XS Rating Curve= 0 ,0
Exp/Cntr(USF)=0,0
Exp/Cntr=0.3,0.1

Type RM Length L Ch R = 1 ,2913    ,310.9,284.3,220.6
XS GIS Cut Line= 5
1630098.66655648461704.851042018 1630261.8118433461794.936959403
 1630261.7086521461917.3217223121630325.37762235461933.935505472
1630438.68155967 461960.04287901
#Sta/Elev= 30
       0  766.07    25.4  759.59    32.9  755.93    49.2  752.52    70.3  744.47
   100.3  734.23   114.4  730.28   133.7  726.04   156.5   718.4   160.3  716.66
   167.5     712   171.5  710.48   175.3  709.82  203.45  708.61   229.5  708.03
283.4407 708.636   304.9  711.22   359.9  714.57     365  715.53   370.4  717.27
   383.5  722.93   390.3  725.22   403.7  726.13   413.8  727.65   450.9  729.47
   454.2  730.26     461  732.92   465.9  734.04   477.8  736.08   490.8   737.6
#Mann= 5 ,-1,0
       0      .1       0     120     .06       0  203.45    .045       0
283.4407     .06       0  434.55     .05       0
Bank Sta=203.45,283.4407
XS Rating Curve= 0 ,0
Exp/Cntr(USF)=0,0
Exp/Cntr=0.3,0.1

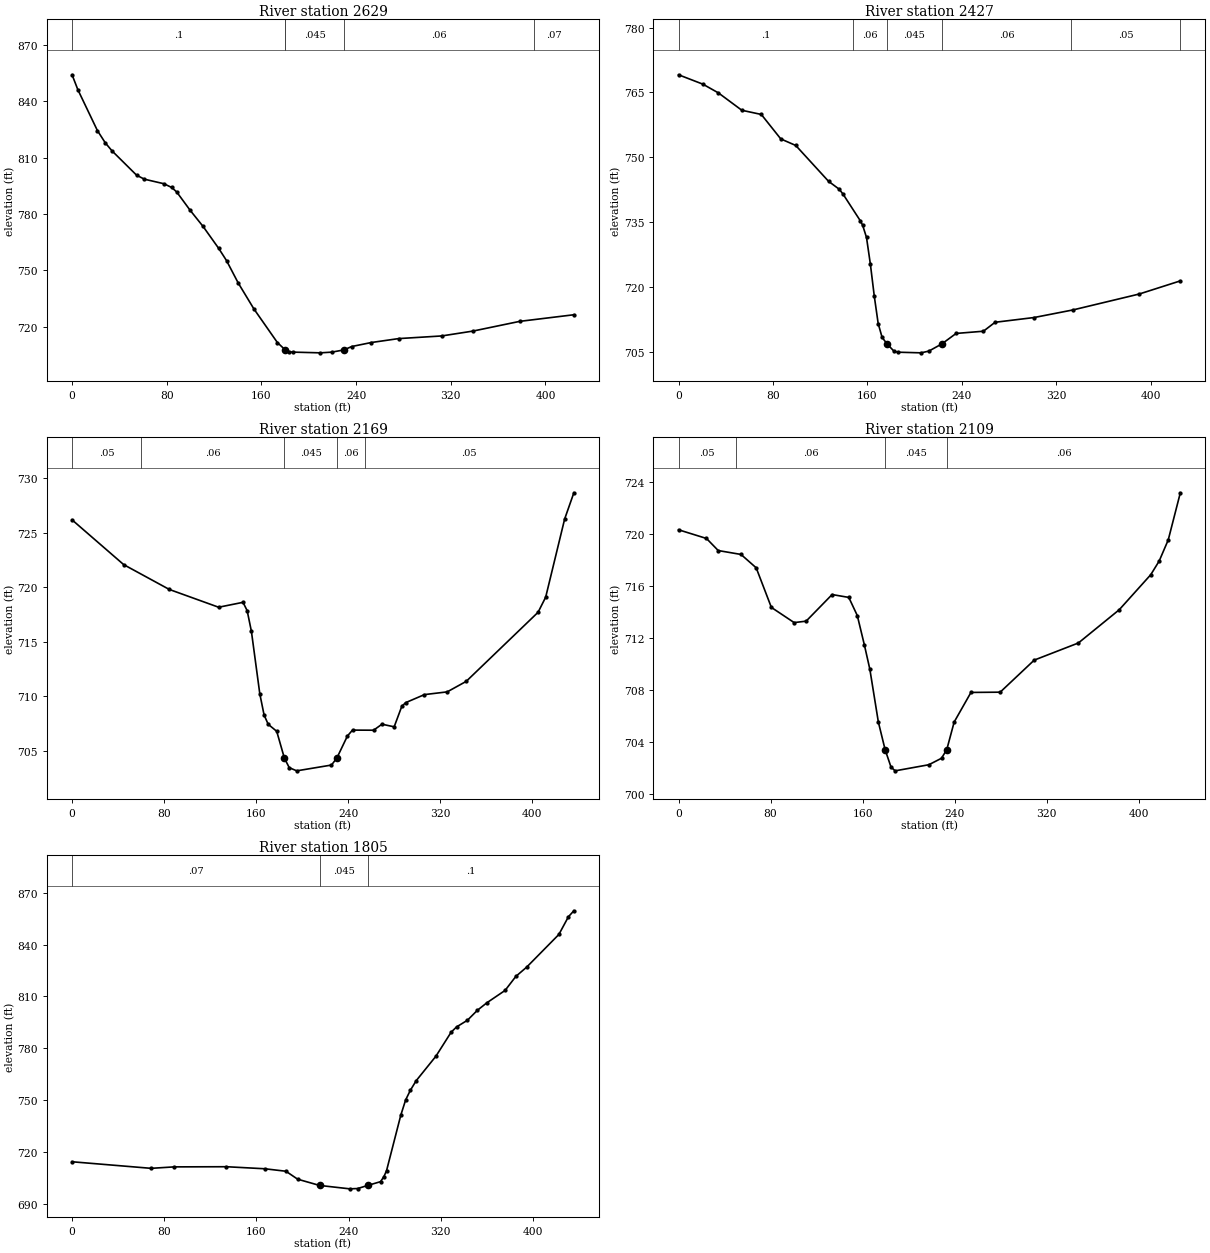
Type RM Length L Ch R = 1 ,2629    ,207.5,202.5,196.6
XS GIS Cut Line= 2
1629965.07338785462071.0191172411630385.95315508 462122.41419298
#Sta/Elev= 30
       0  854.13     4.9  846.17    21.4  824.44    28.1  817.87    33.8   813.6
    54.5  800.69    61.1  798.55    77.6  796.13    84.2  794.13    88.4  791.76
    99.7  782.05   110.7  773.39   123.9  761.71   130.5  755.23   140.4  743.28
   153.6  729.53   173.5  711.58   180.1  707.69   183.4   706.7   186.7  706.49
   209.8  706.11   219.4  706.48   229.7  707.66   236.3  709.47   252.8   711.6
   275.9  713.69   312.3   715.1   338.7  717.69   378.3  722.87     424  726.38
#Mann= 5 ,-1,0
       0      .1       0     180     .06       0   180.1    .045       0
   229.7     .06       0     390     .07       0
Bank Sta=180.1,229.7
XS Rating Curve= 0 ,0
Exp/Cntr(USF)=0,0
Exp/Cntr=0.3,0.1

Type RM Length L Ch R = 1 ,2427    ,266.7,258,250.9
XS GIS Cut Line= 6
1629965.85312526462318.4339286691630052.84606151462309.028435677
1630127.41152917462300.9667720051630226.83226208462290.218105838
1630301.39772975462282.1564421651630388.39066601462272.751277253
#Sta/Elev= 30
       0  769.09    20.6  766.92    33.8  764.89    53.6  760.88    70.1  759.91
    86.6  754.25    99.3  752.73   127.1  744.43   136.1  742.61   139.4  741.45
   153.9  735.33   155.9   734.3   159.2  731.45   162.5  725.24   165.8  717.85
   169.1  711.52   172.4  708.34  176.61706.8151   182.3  705.18   185.6   704.9
   205.4  704.75     212  705.15  223.01706.8151   235.1  709.24   258.2  709.75
   268.1  711.82   301.1  712.92   334.1  714.68   390.2  718.36     425   721.4
#Mann= 6 ,-1,0
       0      .1       0   147.5     .06       0  176.61    .045       0
  223.01     .06       0   332.5     .05       0     425     .06       0
Bank Sta=176.61,223.01
XS Rating Curve= 0 ,0
Exp/Cntr(USF)=0,0
Exp/Cntr=0.3,0.1

Type RM Length L Ch R = 1 ,2169    ,62.6,60.2,59.8
XS GIS Cut Line= 4
1629997.48668736462600.2338434381630131.14729504462586.164305788
1630258.77810086462522.8513863631630417.56288291462509.786815688
#Sta/Elev= 30
       0  726.16    44.9  722.06    84.5  719.79   127.4  718.16   148.6  718.61
   152.2  717.85   155.9  715.95   163.2  710.23   166.9   708.3   170.5  707.44
   177.9   706.8  184.54  704.35   188.8  703.47   195.3  703.18   225.5  703.71
  230.17704.3511   239.4  706.38   243.8  706.91   262.1   706.9   269.4  707.45
     280  707.21   286.6  709.08   289.9  709.42   306.3  710.16   326.1  710.41
   342.6  711.37   405.1   717.7   411.7  719.08   428.2  726.24   436.2  728.64
#Mann= 5 ,-1,0
       0     .05       0      60     .06       0  184.54    .045       0
  230.17     .06       0   254.4     .05       0
Bank Sta=184.54,230.17
XS Rating Curve= 0 ,0
Exp/Cntr(USF)=0,0
Exp/Cntr=0.3,0.1

Type RM Length L Ch R = 1 ,2109    ,267.8,303.4,326.9
XS GIS Cut Line= 4
1630004.52145619462660.5318619381630138.18206386462646.462324288
1630265.81286969462583.1494048631630424.59765174462570.084834188
#Sta/Elev= 30
       0  720.32    24.3  719.65    34.5  718.72    54.3  718.42    67.5  717.39
    80.7  714.34   100.5  713.17   110.9  713.28   133.5  715.33     148  715.11
   155.4  713.71   161.6  711.43   166.3  709.58   173.7  705.51  179.55703.3895
   184.7  702.04   188.3  701.75   217.6  702.22   228.6  702.72  233.18703.3871
   239.6  705.51   254.2  707.79   279.6  707.81   309.2  710.28   347.6   711.6
   383.1  714.16   410.5  716.86   417.8  717.91   425.7  719.54   436.2  723.17
#Mann= 4 ,-1,0
       0     .05       0      50     .06       0  179.55    .045       0
  233.18     .06       0
Bank Sta=179.55,233.18
XS Rating Curve= 0 ,0
Exp/Cntr(USF)=0,0
Exp/Cntr=0.3,0.1

Type RM Length L Ch R = 1 ,1805    ,298.9,304.7,307.9
XS GIS Cut Line= 6
1630002.15718651 462729.044327931630081.75020318462784.255831674
1630138.21695375462835.3518580941630199.61184409462914.286411509
1630245.65768376462973.4877366721630299.37739259463042.555840001
#Sta/Elev= 30
       0  714.46    68.6  710.66    88.6   711.5     134  711.59   167.3  710.41
   185.6  708.98   195.8  704.38   214.8700.7783     241  698.81   247.9  698.99
  256.54700.7772   267.7  702.95   270.6  705.82   272.9  709.24   285.3  741.38
   289.5  750.19   293.6  755.76   298.6  761.26   315.8  775.48     329  789.35
   333.7  792.39   343.1  796.23   351.8  802.03   360.1  806.39   375.8  813.48
   385.2  821.62   394.5  826.92   422.5  845.84   430.8  856.09   435.5  859.52
#Mann= 3 ,-1,0
       0     .07       0   214.8    .045       0  256.54      .1       0
Bank Sta=214.8,256.54
XS Rating Curve= 0 ,0
Exp/Cntr(USF)=0,0
Exp/Cntr=0.3,0.1