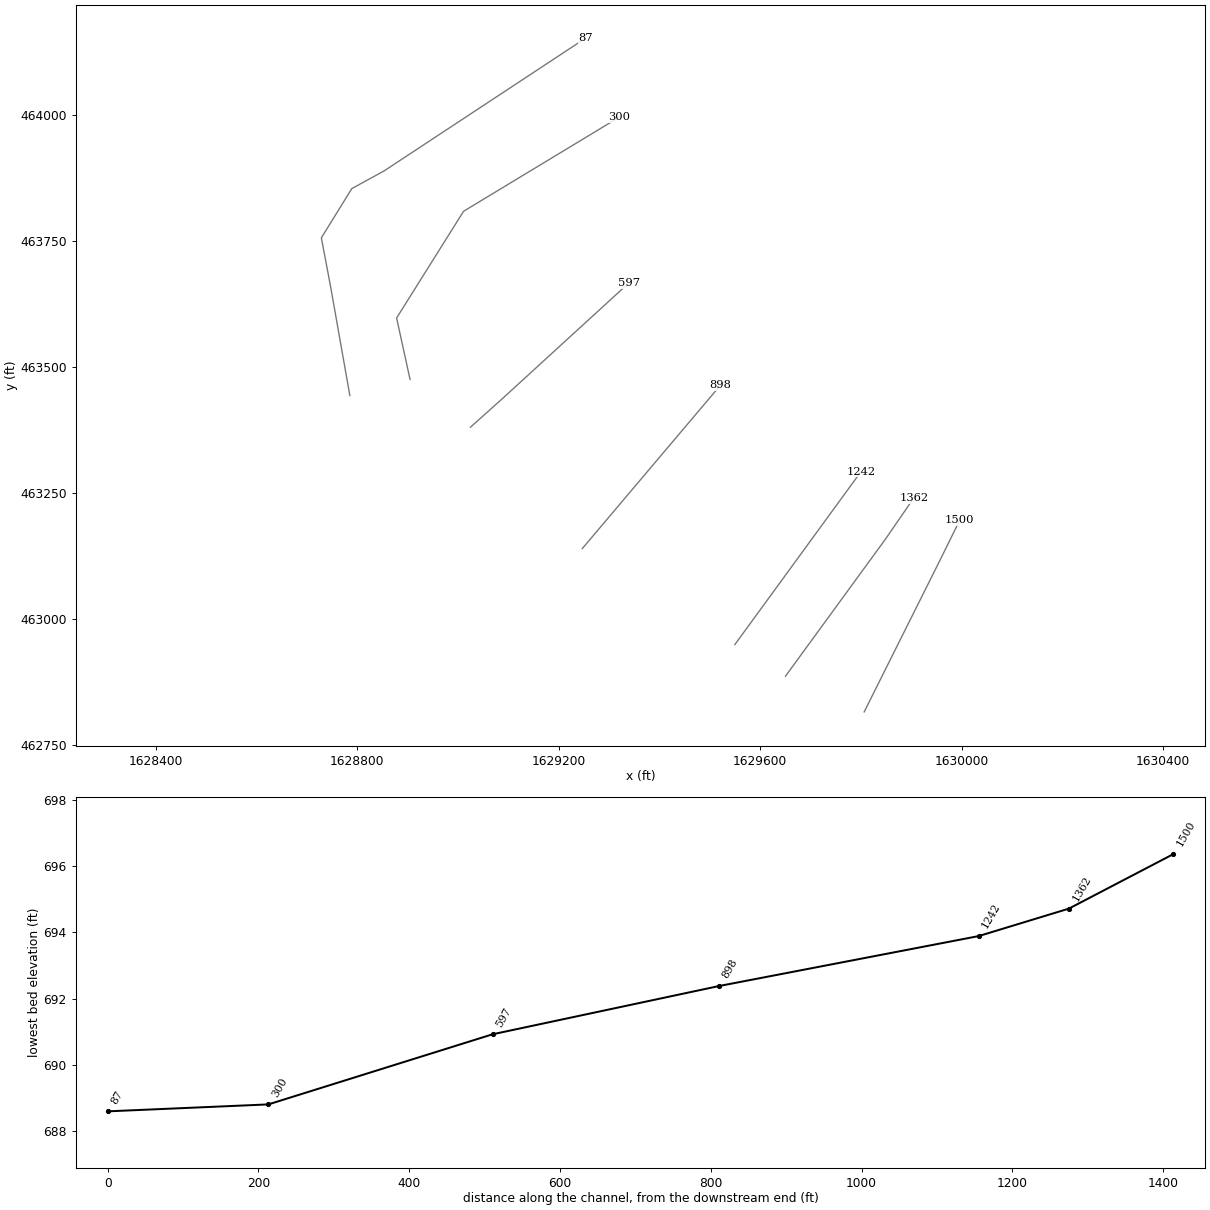
HEC-RAS study LynCmpRn.prj: LynCmpRn

--- LynCmpRn.g01 (geometry) --- (continued)

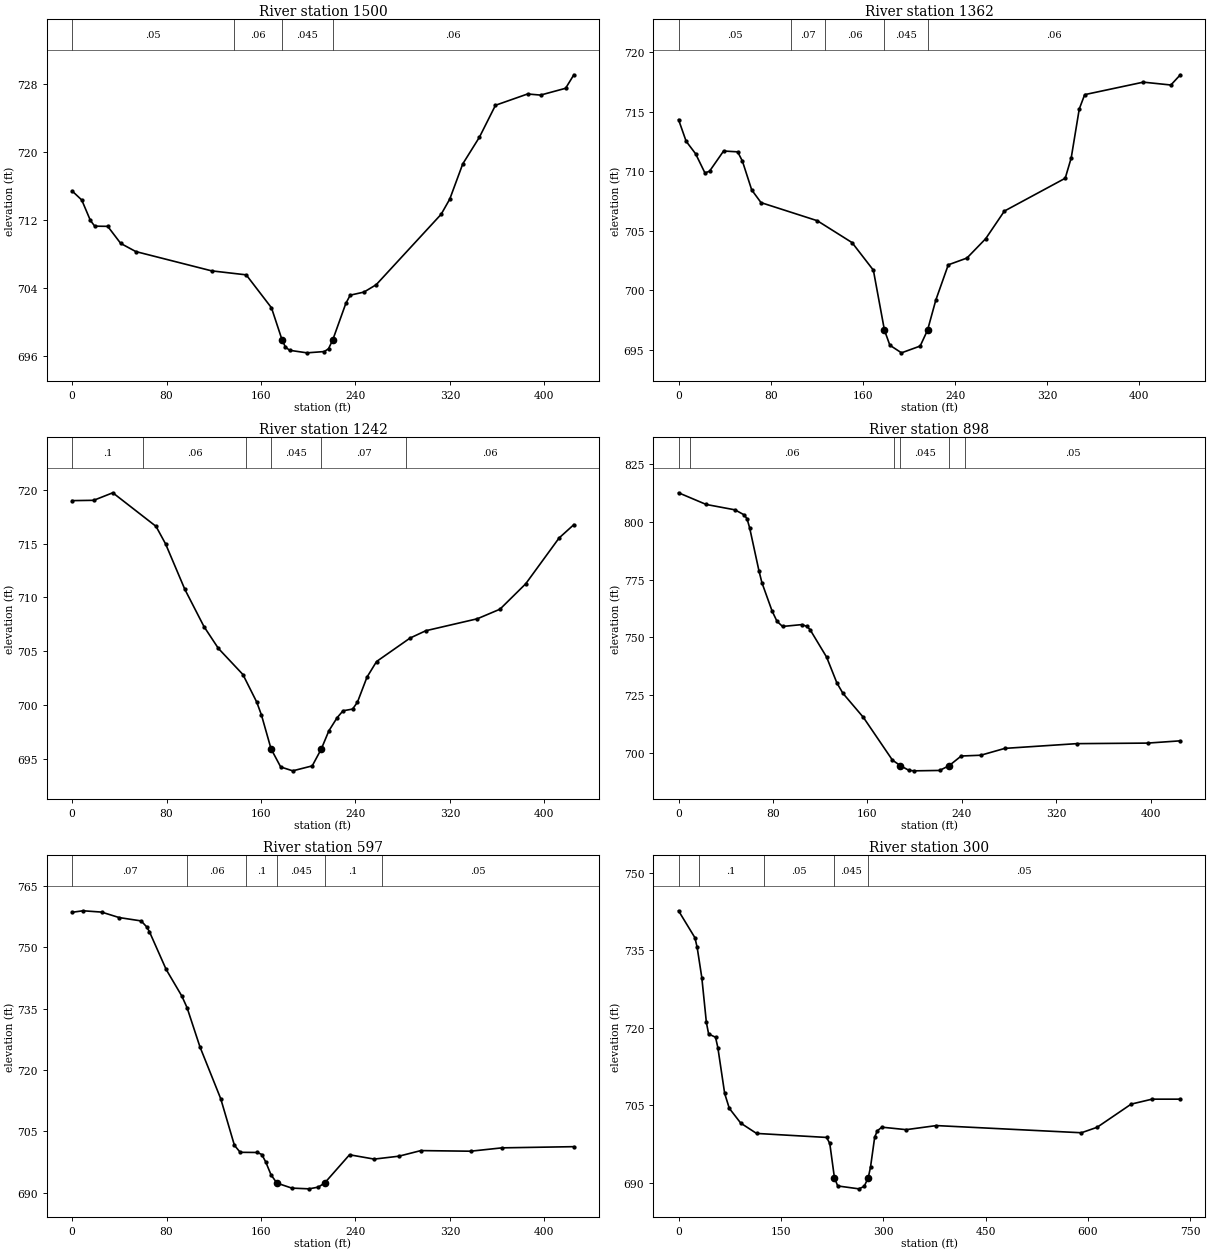
Type RM Length L Ch R = 1 ,1500    ,142.1,138.7,136.3
XS GIS Cut Line= 6
1629806.39051767 462815.002161251629845.52167301462893.264800012
1629879.06261642 462960.346686841629923.78431176463049.789421335
1629957.32525517463116.8713081781629996.01120143463195.356387421
#Sta/Elev= 30
       0  715.43     8.2  714.36    15.5  711.96    19.2  711.28    30.2  711.26
    41.2  709.25      54  708.29   118.2  706.02   147.5  705.55   168.9  701.67
  177.92697.8683   180.6  697.08   184.2  696.67   198.9  696.37   213.6  696.52
   217.2  696.85  220.73697.8705   231.9   702.2   235.6  703.16   247.2  703.52
   257.6  704.39   312.6  712.68   319.9  714.47   330.9  718.61     345  721.75
   358.6  725.51   385.8  726.84   396.8  726.71     418  727.51     425   729.1
#Mann= 4 ,-1,0
       0     .05       0   137.5     .06       0  177.92    .045       0
  220.73     .06       0
Bank Sta=177.92,220.73
XS Rating Curve= 0 ,0
Exp/Cntr(USF)=0,0
Exp/Cntr=0.3,0.1

Type RM Length L Ch R = 1 ,1362    ,119.6,119.6,119
XS GIS Cut Line= 6
 1629650.1262771462885.8386485671629701.70491408462956.520265738
1629745.91545559463017.1044621561629804.86218809463097.883500064
1629849.07272959463158.4676964821629904.67156258463239.198655309
#Sta/Elev= 30
       0  714.33     6.6  712.51    14.8  711.46    22.9  709.85    26.9  709.99
    39.1  711.69    51.3  711.62    55.4  710.85    63.5  708.42    71.6  707.35
   120.4  705.83   150.6  703.99   169.1  701.67   178.7  696.63   183.4  695.36
   193.5  694.72   209.7  695.29  216.12696.6285   223.3  699.16   234.1  702.12
   250.3  702.69   266.6  704.32   282.8  706.64   335.6   709.4   340.8  711.11
   347.8  715.23   352.5  716.43   403.4  717.48   427.3  717.24   435.5   718.1
#Mann= 5 ,-1,0
       0     .05       0    97.5     .07       0   127.5     .06       0
   178.7    .045       0  216.12     .06       0
Bank Sta=178.7,216.12
XS Rating Curve= 0 ,0
Exp/Cntr(USF)=0,0
Exp/Cntr=0.3,0.1

Type RM Length L Ch R = 1 ,1242    ,345.7,344.3,342.8
XS GIS Cut Line= 6
 1629549.6440676462948.6062604991629601.22270459463019.287877669
1629645.43324609463079.872074088 1629704.3799786463160.651111996
 1629748.5905201463221.2353084141629800.16948518463291.916597491
#Sta/Elev= 30
       0     719    18.3  719.03    34.5  719.73    71.1  716.61    79.2  714.98
    95.5  710.76   111.7   707.3   123.9  705.27   144.7  702.84   156.4  700.28
   160.4  699.08  168.53695.9331   176.7  694.25   186.9  693.89   203.4  694.35
  211.15695.9345   217.5  697.61   224.5  698.83   229.5  699.47   237.6  699.63
   241.7  700.27   249.8   702.6   257.9  704.05   286.3  706.23   299.6  706.91
   343.2  708.02   362.4  708.91   384.2  711.27   412.5  715.53     425  716.77
#Mann= 6 ,-1,0
       0      .1       0      60     .06       0   147.5     .07       0
  168.53    .045       0  211.15     .07       0   282.5     .06       0
Bank Sta=168.53,211.15
XS Rating Curve= 0 ,0
Exp/Cntr(USF)=0,0
Exp/Cntr=0.3,0.1

Type RM Length L Ch R = 1 ,898     ,303.4,300.5,298.2
XS GIS Cut Line= 6
1629246.82372342463139.109452665 1629303.3439516463205.905578926
1629351.78972083463263.1597295111629416.38407984463339.498159513
1629464.82984909463396.7519820031629521.34974918463463.548436344
#Sta/Elev= 30
       0  812.46    23.4  807.42    47.8  805.09    55.5  802.95      58  801.26
    60.2  797.38    68.1   778.8    70.6  773.67    79.2  761.45    83.4  756.94
    88.1  754.73   104.4  755.53   108.8  754.76   111.4  753.36   125.4  741.51
   134.1  730.37   139.2  725.88   156.6  715.44   181.2  696.99  187.98694.5986
   195.2  692.56   199.8  692.38   221.1  692.55  229.13 694.598   239.4  698.78
     256  699.12   276.4  702.08   337.2  704.12   397.3  704.36     425  705.34
#Mann= 6 ,-1,0
       0      .1       0      10     .06       0   182.5      .1       0
  187.98    .045       0  229.13      .1       0   242.5     .05       0
Bank Sta=187.98,229.13
XS Rating Curve= 0 ,0
Exp/Cntr(USF)=0,0
Exp/Cntr=0.3,0.1

Type RM Length L Ch R = 1 ,597     ,290.9,297.4,303.2
XS GIS Cut Line= 6
1629024.73952192463379.8009004291629089.95002143463438.151177421
1629145.30194484463488.7590158431629219.10461876463556.235915005
1629274.45654218463606.8437534271629339.03384084463665.886286259
#Sta/Elev= 30
       0  758.53     9.3   758.9      25  758.58    39.9  757.24    58.5  756.42
    63.1     755    65.5   753.8    79.7  744.55      93  738.03    97.4  735.21
   108.3  725.64   125.9  712.96   137.5  701.57   142.4  699.85     157  699.81
   160.7  699.31   164.1  697.45   168.5  694.35   173.5692.3262   186.1   691.1
   200.7  690.92   208.5  691.34  213.87692.3273     235  699.25   255.9  698.19
   276.8   698.9   295.4  700.27   337.5  700.12   364.1  700.94     425  701.23
#Mann= 6 ,-1,0
       0     .07       0   97.51     .06       0  147.51      .1       0
   173.5    .045       0  213.87      .1       0   262.5     .05       0
Bank Sta=173.5,213.87
XS Rating Curve= 0 ,0
Exp/Cntr(USF)=0,0
Exp/Cntr=0.3,0.1

Type RM Length L Ch R = 1 ,300     ,212.7,213.1,212.9
XS GIS Cut Line= 6
1628904.82176339 463474.715741811628878.15943451463596.478288591
1628918.03402667 463660.000143171628971.19993085463744.695511833
  1629011.074523463808.2173664271629319.69084034463994.653216343
#Sta/Elev= 30
       0  742.69      24  737.47    27.3  735.59    34.1  729.74    40.8  721.04
    44.1  718.81    54.2  718.18    57.6  716.17    67.6  707.28    74.4   704.4
    91.2  701.53   114.3  699.54     217  698.76   221.6  697.59  228.39690.9726
   233.2  689.36   264.2   688.8     272  689.27  277.98690.9737   281.3  693.03
   287.4  698.82   291.3  700.06   297.9  700.75   333.6  700.27   377.8  701.06
   590.3  699.67   613.3  700.73   663.2  705.22   693.8  706.18   735.2  706.18
#Mann= 5 ,-1,0
       0     .07       0      30      .1       0  124.65     .05       0
  228.39    .045       0  277.98     .05       0
Bank Sta=228.39,277.98
XS Rating Curve= 0 ,0
Exp/Cntr(USF)=0,0
Exp/Cntr=0.3,0.1

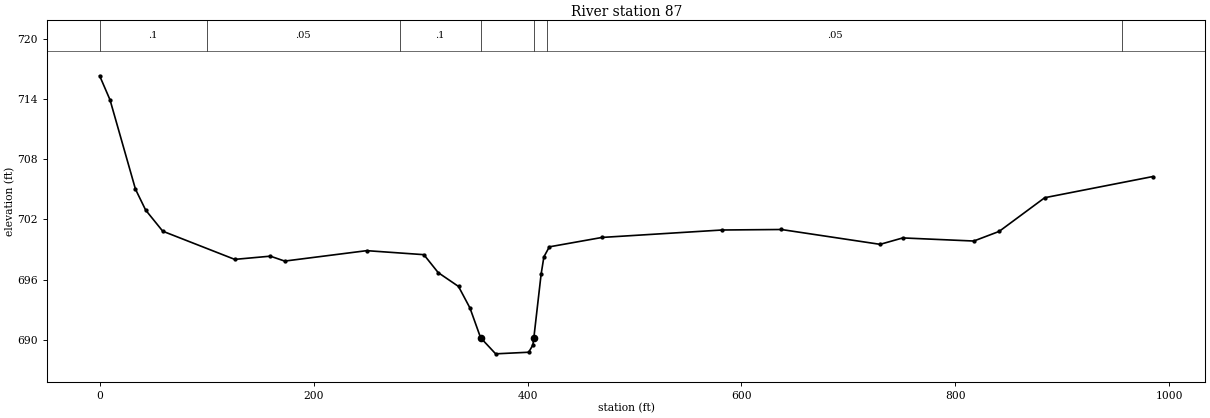
Type RM Length L Ch R = 1 ,87      ,,,
XS GIS Cut Line= 6
1628785.36759588463442.6469399911628746.95010798463659.744933736
 1628728.8011229463755.5753710981628789.29323632463853.295111756
1628853.49807894463888.4165996371629252.99620512464151.497578549
#Sta/Elev= 30
       0  716.32     9.7  713.92    33.5  705.01      43  702.93      59  700.82
   126.3  698.01   159.6  698.33     173  697.84   249.7  698.88   303.1  698.48
   316.5  696.69   335.5  695.31   346.2  693.16  356.14690.1956   370.2  688.59
   401.1  688.75     405  689.47  405.92690.1955   412.7  696.52   415.3  698.26
   420.4  699.26   469.8   700.2   581.9  700.94   637.2  700.99   729.6  699.51
   750.8  700.15   817.2  699.84   840.9   700.8   883.5  704.16   984.5  706.27
#Mann= 7 ,-1,0
       0      .1       0     100     .05       0  280.47      .1       0
  356.14    .045       0  405.92      .1       0     418     .05       0
  956.12     .06       0
Bank Sta=356.14,405.92
XS Rating Curve= 0 ,0
Exp/Cntr(USF)=0,0
Exp/Cntr=0.3,0.1
LCMann Table=0

Chan Stop Cuts=-1
Use User Specified Reach Order=0
Composite Channel Slope=5